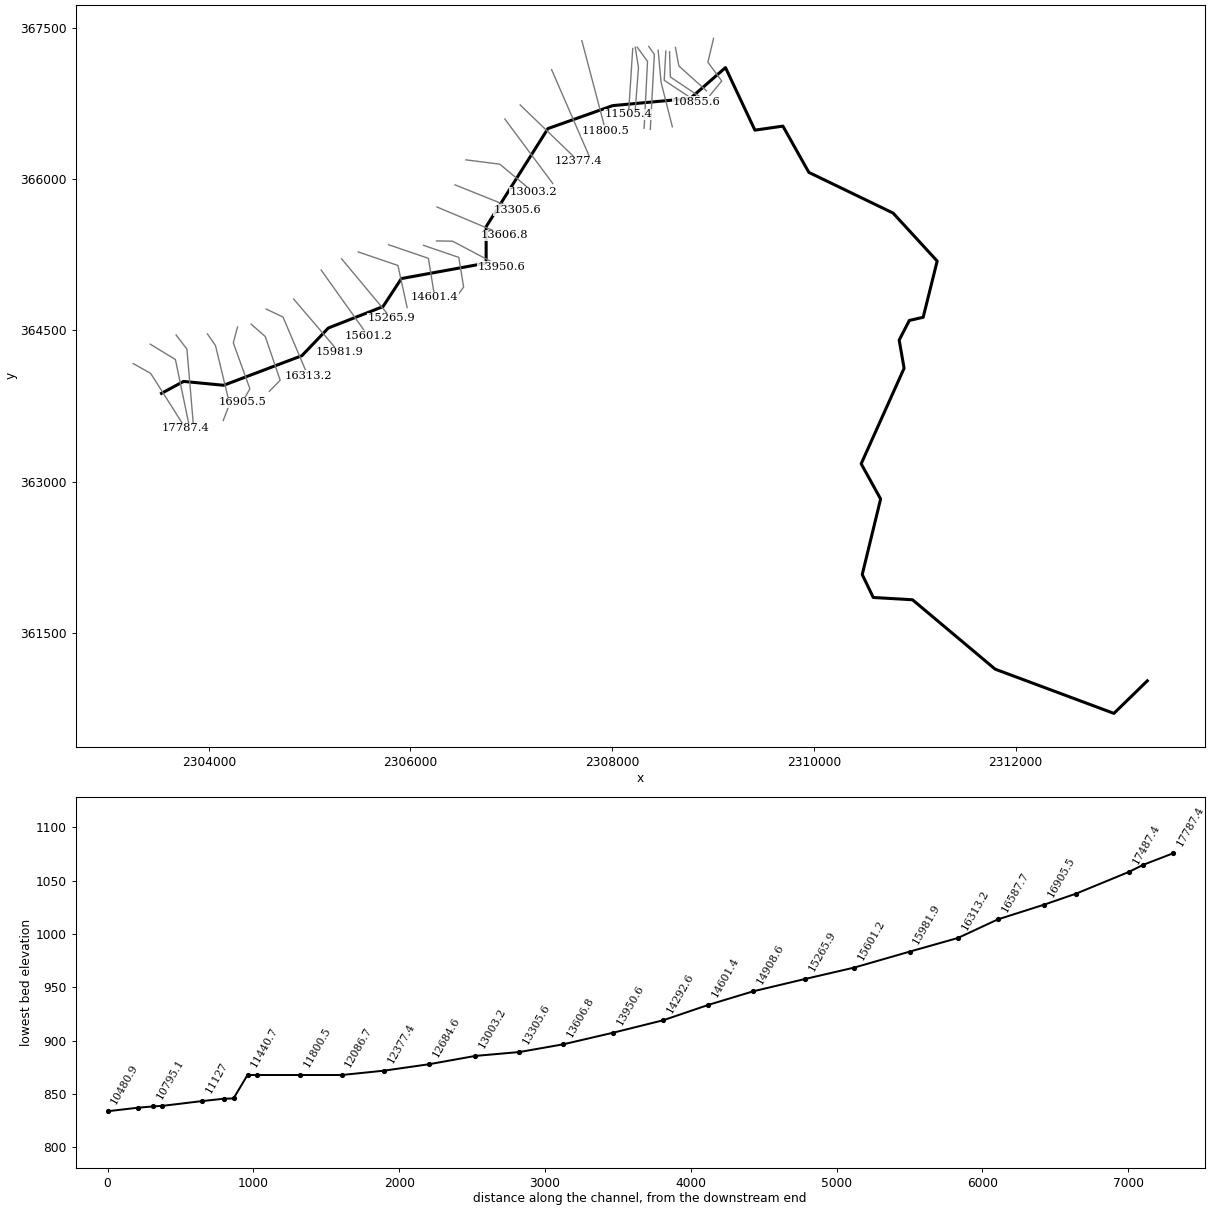
--- SFKINDNCRK.prj (project) ---

Proj Title=SFKINDNCRK
Current Plan=p01
Geom File=g01
Flow File=f01
Plan File=p01
DSS Export Rating Curves=0
DSS Export Rating Curve Sorted=0
DSS Export Volume Flow Curves=0
DXF OffsetX=0
DXF OffsetY=0
DXF ScaleX=0
DXF ScaleY=0

--- SFKINDNCRK.p01 (plan) ---

Plan Title=Floodplain
Program Version=4.00
Geom File=g01
Flow File=f01
K Sum by GR=0
Std Step Tol=0.01
Critical Tol=0.01
Num of Std Step Trials=20
Max Error Tol=0.3
Flow Tol Ratio=0.001
Split Flow NTrial=30
Split Flow Tol=0.02
Split Flow Ratio=0.02
Log Output Level=0
Friction Slope Method=1
Unsteady Friction Slope Method=2
Unsteady Bridges Friction Slope Method=1
Global Log Level=0
CheckData=False
Run HTab=0
Run UNet=0
Run PostProcess=0
UNET Theta=0
UNET Theta Warmup=0
UNET ZTol=0
UNET ZSATol=0
UNET MxIter=0
UNET MaxInSteps=0
UNET DtIC=0
UNET DtMin=0
UNET MaxCRTS=0
UNET WFStab=0
UNET SFStab=0
UNET WFX=0
UNET SFX=0
UNET DSS MLevel=0
UNET DZMax Abort=0
UNET Convert EG Bridges=0
UNET Use Existing IB Tables=0
UNET Froude Limit=0
UNET Froude Power=0
Write IC File=0
Echo Input=False
Echo Output=False
Write Detailed=0

--- SFKINDNCRK.f01 (steady flow) ---

Flow Title=NFF Regression Equation
Program Version=4.00
Number of Profiles=1
Profile Names=P100yr
River Rch & RM=SFKINDNCRK,Main      ,17787.4
504.2432
River Rch & RM=SFKINDNCRK,Main      ,17582.6
581.6929
River Rch & RM=SFKINDNCRK,Main      ,17125.8
604.9322
River Rch & RM=SFKINDNCRK,Main      ,14292.6
646.9860
River Rch & RM=SFKINDNCRK,Main      ,13950.6
764.0070
River Rch & RM=SFKINDNCRK,Main      ,12086.7
779.7095
River Rch & RM=SFKINDNCRK,Main      ,11800.5
922.2208
River Rch & RM=SFKINDNCRK,Main      ,11505.4
1101.458
River Rch & RM=SFKINDNCRK,Main      ,10480.9
1110.928
River Rch & RM=SFKINDNCRK,Main      ,3859
1229.570
River Rch & RM=SFKINDNCRK,Main      ,3544.4
1406.307
River Rch & RM=SFKINDNCRK,Main      ,1019.4
1435.133
River Rch & RM=SFKINDNCRK,Main      ,768.7
1438.829
Boundary for River Rch & Prof#=SFKINDNCRK,Main      ,1
Up Type=0
Dn Type=3
Dn Slope=0.008604

--- SFKINDNCRK.g01 (geometry) ---

Geom Title=USGS 10m DEM
Program Version=5.03

River Reach=SFKINDNCRK      ,Main
Reach XY= 30
     2303531.603      363877.354     2303750.353      363995.409
     2304147.922      363957.215     2304923.964      364250.618
     2305186.117      364524.923     2305727.783      364736.729
     2305910.075      365014.506     2306750.353      365167.284
     2306750.353      365528.396       2307363.2      366500.618
     2308005.561      366728.048     2308774.659      366799.229
     2309123.617      367104.784     2309415.284      366484.993
     2309693.061      366524.923     2309950.006       366066.59
     2310785.075      365663.812     2311222.575      365188.118
     2311083.686      364630.826     2310946.533      364599.576
     2310845.839      364405.132      2310894.45      364125.618
     2310469.103      363179.437     2310661.811      362830.479
      2310479.52      362082.215     2310588.894      361854.784
     2310977.783      361832.215     2311797.228      361144.715
     2312975.006       360706.52     2313305.948      361028.686

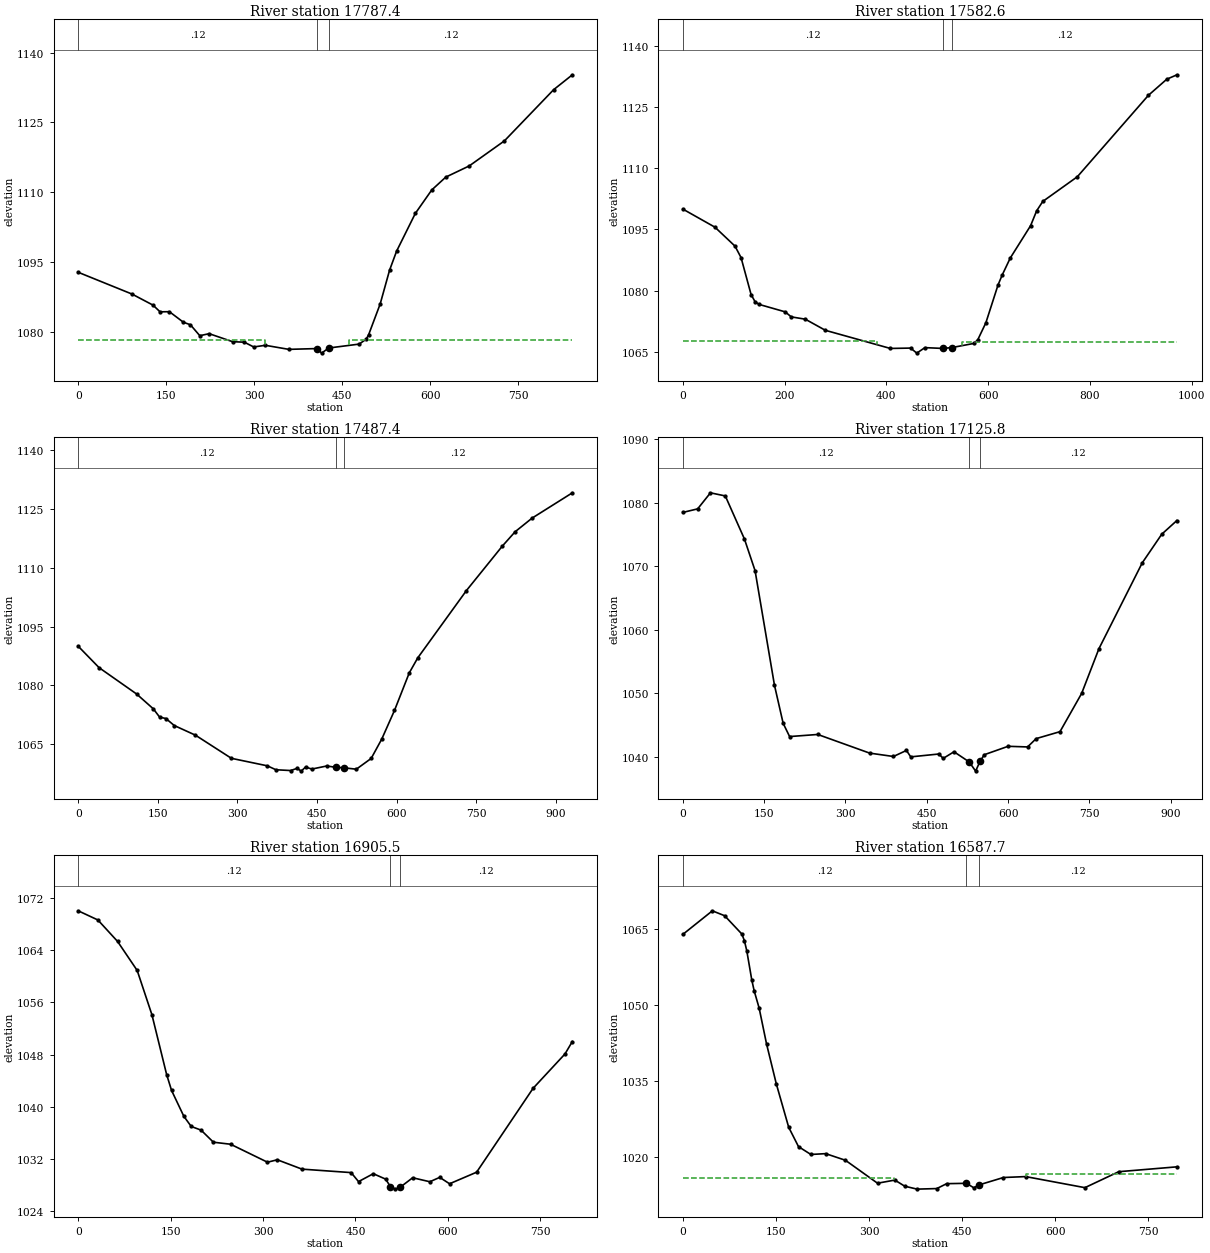
Type RM Length L Ch R = 1 ,17787.4 ,212.8,204.8,196.6
XS GIS Cut Line= 3
     2303250.472      364172.627     2303424.114      364075.198
     2303768.363      363532.335
#Sta/Elev= 30
       0 1092.78    91.6  1088.1   127.4 1085.72   139.4 1084.28   155.3 1084.31
   179.2 1082.04   191.1  1081.5   207.1 1079.15   223.1 1079.58     263 1077.86
     283 1077.75   298.9 1076.73   318.9 1077.08   358.8 1076.21   406.7 1076.38
   414.7  1075.4   426.7  1076.5   478.6 1077.34   490.6 1078.39   494.6 1079.29
   514.5 1085.98   530.5 1093.24   542.5 1097.34   574.4 1105.45   602.4 1110.49
   626.3 1113.25   666.2 1115.65   726.1 1121.03     810 1132.04   841.9 1135.24
#Mann= 3 ,-1 , 0
       0     .12       0   406.7    .045       0   426.7     .12       0
#XS Ineff= 2 , 0
          318.87  1078.2  462.11         1078.31
Permanent Ineff=
       F       F
Bank Sta=406.7,426.7
XS Rating Curve= 0 ,0
Exp/Cntr=0.3,0.1

Type RM Length L Ch R = 1 ,17582.6 ,97.9,95.2,92.5
XS GIS Cut Line= 3
     2303419.945      364364.368     2303669.448      364212.537
     2303808.027       363547.87
#Sta/Elev= 30
       0    1100    63.2 1095.55   102.6  1090.9   114.5 1088.08   134.2 1079.01
   142.1 1077.23     150 1076.59   201.3 1074.76   213.1 1073.53   240.8 1072.96
   280.2 1070.23   407.9 1065.78   447.8 1065.87   459.8 1064.63   475.8 1065.98
   511.7 1065.78   529.4 1066.01   571.6    1067   579.6 1067.89   595.6 1072.08
   619.6  1081.4   627.6 1083.78   643.5 1087.97   683.5 1095.92   695.4 1099.57
   707.4 1101.87   775.3 1107.93   915.1 1127.94   951.1 1131.88     971 1132.96
#Mann= 3 ,-1 , 0
       0     .12       0   511.7    .045       0   529.4     .12       0
#XS Ineff= 2 , 0
          382.15 1067.54  547.75         1067.48
Permanent Ineff=
       F       F
Bank Sta=511.7,529.4
XS Rating Curve= 0 ,0
Exp/Cntr=0.3,0.1

Type RM Length L Ch R = 1 ,17487.4 ,358.1,361.6,365.2
XS GIS Cut Line= 3
     2303676.114      364455.636     2303783.623      364315.066
     2303847.691      363563.405
#Sta/Elev= 30
       0    1090    39.3 1084.54   110.1 1077.81   141.6 1074.02   153.4 1071.92
   165.2 1071.56     181 1069.77   220.9 1067.31   288.7  1061.4   356.6 1059.48
   372.6 1058.48   400.5 1058.28   412.5 1058.84   420.4 1058.13   428.4 1059.17
   440.4 1058.66   468.4 1059.44     486  1059.1     501 1058.98   524.2 1058.62
   552.2 1061.37   572.1  1066.3   596.1 1073.61     624 1083.21     640 1087.04
   731.8 1104.23   799.6  1115.6   823.6 1119.24   855.5 1122.71   931.4 1129.17
#Mann= 3 ,-1 , 0
       0     .12       0     486    .045       0     501     .12       0
Bank Sta=486,501
XS Rating Curve= 0 ,0
Exp/Cntr=0.3,0.1

Type RM Length L Ch R = 1 ,17125.8 ,217.8,220.3,222.6
XS GIS Cut Line= 4
     2303986.608      364466.418     2304066.942      364350.327
     2304206.713      363772.537     2304143.708      363608.538
#Sta/Elev= 30
       0 1078.44    27.4    1079      51 1081.52    78.4 1081.03   113.7 1074.26
   133.3 1069.29   169.1 1051.28   185.1 1045.31     197 1043.23   248.9 1043.56
   344.6 1040.63   388.5  1040.1   412.5 1041.05   420.4 1040.04   472.3 1040.49
   480.3  1039.8   500.2 1040.84   528.2 1039.25   540.1  1037.8   548.1 1039.32
   556.1 1040.38     600  1041.7   635.9  1041.6   651.8 1042.91   695.7    1044
   735.6    1050   767.6 1057.05   847.4 1070.52   883.4 1075.02   911.3 1077.17
#Mann= 3 ,-1 , 0
       0     .12       0   528.2    .045       0   548.1     .12       0
Bank Sta=528.2,548.1
XS Rating Curve= 0 ,0
Exp/Cntr=0.3,0.1

Type RM Length L Ch R = 1 ,16905.5 ,318.3,317.7,317.2
XS GIS Cut Line= 4
     2304285.433      364535.218     2304243.391      364377.261
     2304407.956      363922.873     2304332.241      363787.163
#Sta/Elev= 30
       0    1070    31.9  1068.6    63.8 1065.32    95.7 1060.87   119.6  1054.1
   143.5 1044.94   151.5 1042.51   171.4 1038.56   183.4    1037   199.4 1036.44
   219.4 1034.59   247.3 1034.28   307.2 1031.53   323.2  1031.9   363.2 1030.47
     443 1029.94     455 1028.56     479 1029.77     499 1028.94   506.9 1027.78
   514.9 1027.41   522.9 1027.72   542.9 1029.15   570.8 1028.54   586.8 1029.21
   602.8 1028.23   646.7    1030   738.4 1042.84   790.2  1048.1   802.1    1050
#Mann= 3 ,-1 , 0
       0     .12       0   506.9    .045       0   522.9     .12       0
Bank Sta=506.9,522.9
XS Rating Curve= 0 ,0
Exp/Cntr=0.3,0.1

Type RM Length L Ch R = 1 ,16587.7 ,272.4,274.5,276.7
XS GIS Cut Line= 4
     2304420.114      364562.721      2304560.54      364440.111
     2304708.114      364007.039     2304601.949      363898.168
#Sta/Elev= 30
       0    1064    47.6 1068.67    67.4  1067.7    95.2 1064.07    99.2 1062.77
   103.1 1060.75   111.1 1055.01     115 1052.83     123 1049.42   134.9 1042.34
   150.7  1034.4   170.6 1025.84   186.4 1022.01   206.3 1020.46   230.2 1020.62
     262 1019.31   313.7 1014.77   341.6 1015.39   357.5 1014.18   377.4  1013.6
   409.2 1013.71   425.1 1014.68     457 1014.75   468.9 1013.86   476.8 1014.42
   516.6  1015.9   552.4 1016.08   647.8 1013.89   702.4 1017.05     796 1018.01
#Mann= 3 ,-1 , 0
       0     .12       0     457    .045       0   476.8     .12       0
#XS Ineff= 2 , 0
          340.58 1015.87  552.18         1016.64
Permanent Ineff=
       F       F
Bank Sta=457,476.8
XS Rating Curve= 0 ,0
Exp/Cntr=0.3,0.1

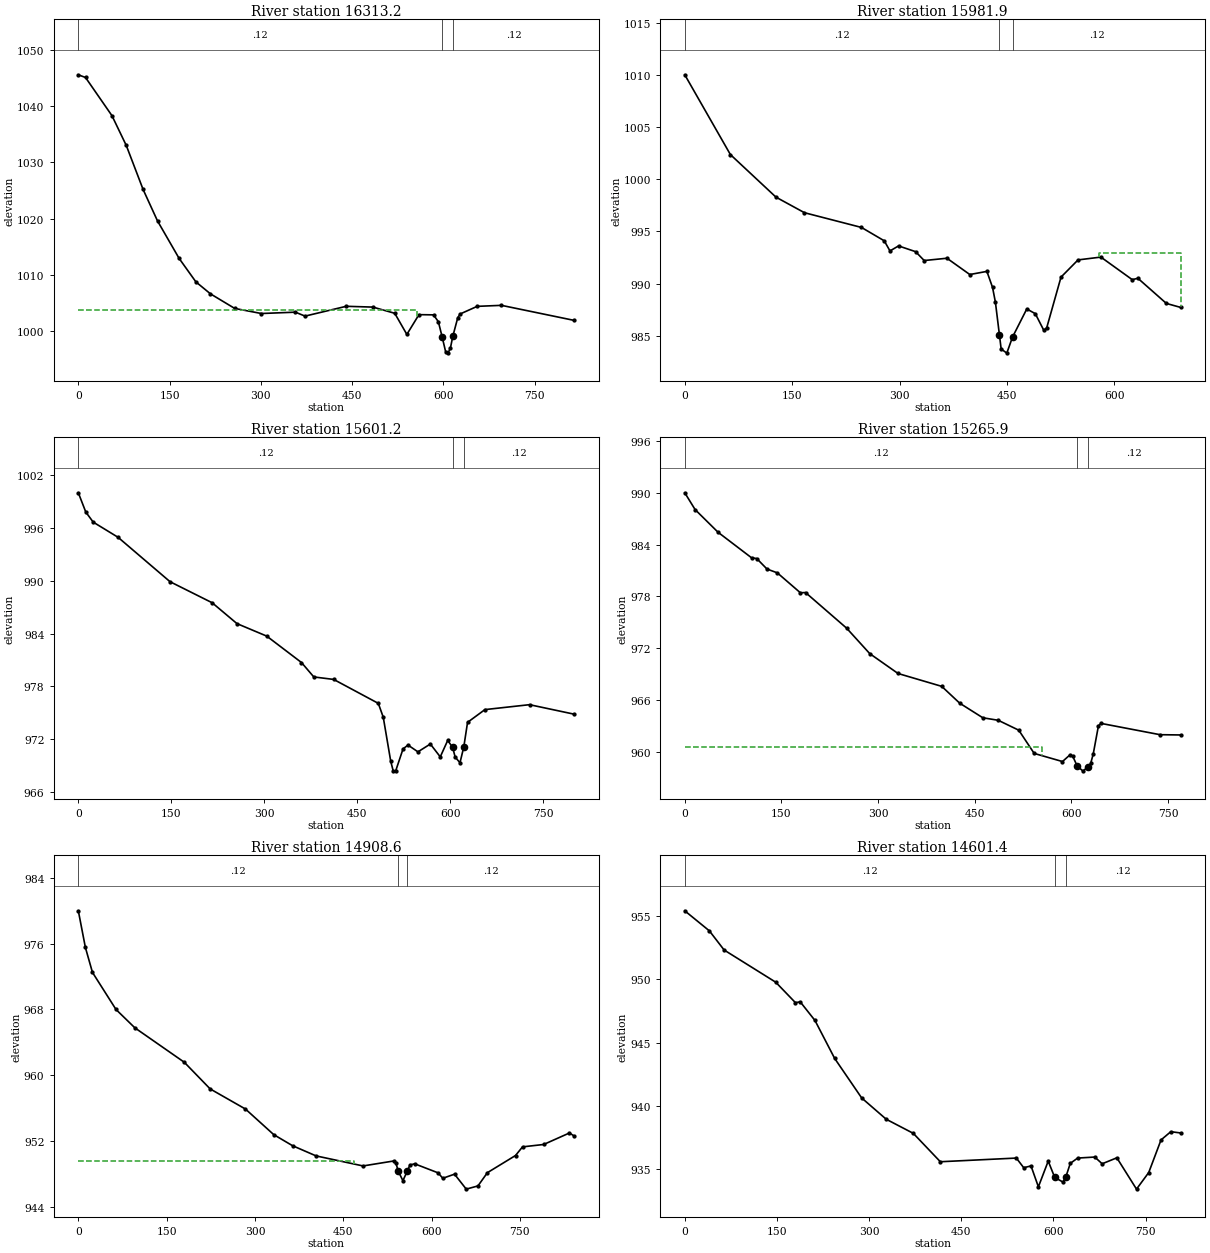
Type RM Length L Ch R = 1 ,16313.2 ,324.4,331.3,338.2
XS GIS Cut Line= 3
     2304569.381      364712.705     2304736.509      364632.777
     2304982.409      364053.393
#Sta/Elev= 30
       0 1045.54    11.8 1045.07    55.2  1038.3    78.8    1033   106.4  1025.2
   130.1 1019.61   165.6 1012.96   193.2 1008.79   217.1 1006.67     257 1004.08
   300.8 1003.18   356.6 1003.42   372.5 1002.72   440.2 1004.46     484 1004.32
   519.9 1003.22   539.8  999.47   559.7 1002.98   583.6 1002.94   591.6 1001.72
  597.75999.0428   603.5  996.41   607.5  996.15   611.5  997.12   615.3  999.13
   623.4 1002.42   627.4  1003.1   655.3 1004.45   695.2 1004.63   814.7 1001.96
#Mann= 3 ,-1 , 0
       0     .12       0  597.75    .045       0   615.3     .12       0
#XS Ineff= 2 , 0
          557.28 1003.89
Permanent Ineff=
       F       F
Bank Sta=597.75,615.3
XS Rating Curve= 0 ,0
Exp/Cntr=0.3,0.1

Type RM Length L Ch R = 1 ,15981.9 ,383.4,380.7,377.7
XS GIS Cut Line= 2
     2304841.736      364811.809     2305291.856      364285.358
#Sta/Elev= 30
       0    1010    63.7 1002.36   127.4  998.28   167.2  996.79   246.8  995.38
   278.6   994.1   286.6  993.13   298.6  993.61   322.4  993.06   334.4  992.21
   366.2  992.43   398.1  990.87     422  991.17   429.9  989.63   433.9  988.21
  439.53985.0632   441.9  983.74   449.8  983.34   457.8  984.88   477.7  987.57
   489.6  987.12   501.6  985.51   505.6  985.78   525.5  990.62   549.3  992.27
   581.2  992.54     625  990.38   632.9  990.51   672.7   988.1   692.6  987.72
#Mann= 3 ,-1 , 0
       0     .12       0  439.53    .045       0   457.8     .12       0
#XS Ineff= 2 , 0
                          578.64          992.97
Permanent Ineff=
       F       F
Bank Sta=439.53,457.8
XS Rating Curve= 0 ,0
Exp/Cntr=0.3,0.1

Type RM Length L Ch R = 1 ,15601.2 ,334.2,335.3,336.3
XS GIS Cut Line= 2
     2305114.329       365099.31     2305578.416      364448.343
#Sta/Elev= 30
       0    1000      12  997.82      24  996.67      64  994.95   147.9   989.9
   215.8  987.51   255.8  985.14   303.8  983.72   359.8  980.72   379.7  979.08
   411.7   978.8   483.7  976.08   491.7   974.5   503.7  969.51   507.7  968.41
   511.6  968.38   523.6  970.91   531.6  971.34   547.6  970.57   567.6  971.46
   583.6     970   595.6  971.87   603.6  971.07   607.6  969.98   615.4  969.33
  621.51971.1216   627.6  973.92   655.6  975.37   727.5  975.93   799.5  974.85
#Mann= 3 ,-1 , 0
       0     .12       0   603.6    .045       0  621.51     .12       0
Bank Sta=603.6,621.51
XS Rating Curve= 0 ,0
Exp/Cntr=0.3,0.1

Type RM Length L Ch R = 1 ,15265.9 ,368.1,357.3,346.4
XS GIS Cut Line= 2
     2305317.507      365209.975     2305810.399       364618.94
#Sta/Elev= 30
       0  990.01      16  988.07    51.8  985.43   103.7  982.48   111.6   982.4
   127.6  981.18   143.6  980.74   179.4  978.43   187.4  978.46   251.2  974.33
   287.1  971.38     331  969.08   398.8  967.59   426.7  965.64   462.6  963.95
   486.5  963.66   518.4  962.51   542.3  959.82   586.2  958.88   598.1  959.67
   602.1  959.51  608.91958.3777   618.1  957.77     626   958.3     630  958.66
     634  959.77     642  963.01     646   963.3   737.7  961.99   769.6  961.96
#Mann= 3 ,-1 , 0
       0     .12       0  608.91    .045       0     626     .12       0
#XS Ineff= 2 , 0
          553.97  960.61
Permanent Ineff=
       F       F
Bank Sta=608.91,626
XS Rating Curve= 0 ,0
Exp/Cntr=0.3,0.1

Type RM Length L Ch R = 1 ,14908.6 ,308.3,307.2,306.1
XS GIS Cut Line= 3
     2305482.157      365278.494     2305875.741      365144.164
     2305967.111       364727.75
#Sta/Elev= 30
       0     980      12  975.54      24  972.51      64     968      96  965.77
     180  961.58   223.9  958.34   283.9  955.89   331.9  952.78   363.9  951.43
   403.9  950.19   483.6  948.97   535.4  949.57   539.4  949.34   543.4  948.33
   551.3  947.18   559.1  948.39   563.3  949.09   571.3  949.23   611.1  948.13
   619.1  947.47     639  947.97   658.9  946.15   678.8  946.54   694.8  948.15
   742.6  950.24   754.5  951.29   790.4  951.58   834.2  952.98   842.2  952.61
#Mann= 3 ,-1 , 0
       0     .12       0   543.4    .045       0   559.1     .12       0
#XS Ineff= 2 , 0
          467.42  949.52
Permanent Ineff=
       F       F
Bank Sta=543.4,559.1
XS Rating Curve= 0 ,0
Exp/Cntr=0.3,0.1

Type RM Length L Ch R = 1 ,14601.4 ,308.9,308.8,308.7
XS GIS Cut Line= 3
     2305784.285      365349.416     2306177.869      365215.086
     2306240.413      364829.002
#Sta/Elev= 30
       0   955.4      40  953.82      64  952.31     148  949.77     180  948.16
   187.9  948.22   211.9  946.75   243.9  943.76   287.9  940.64   327.9  938.96
   371.9  937.85   415.9  935.61   539.6   935.9   551.6  935.14   563.5  935.28
   575.5  933.63   591.5  935.66   602.1  934.37   615.4  934.01  620.15934.4094
   627.4  935.48   639.4   935.9   667.3  935.98   679.3  935.45   703.2  935.92
   735.2  933.45   755.1  934.76   775.1  937.33     791  937.98     807  937.88
#Mann= 3 ,-1 , 0
       0     .12       0   602.1    .045       0  620.15     .12       0
Bank Sta=602.1,620.15
XS Rating Curve= 0 ,0
Exp/Cntr=0.3,0.1

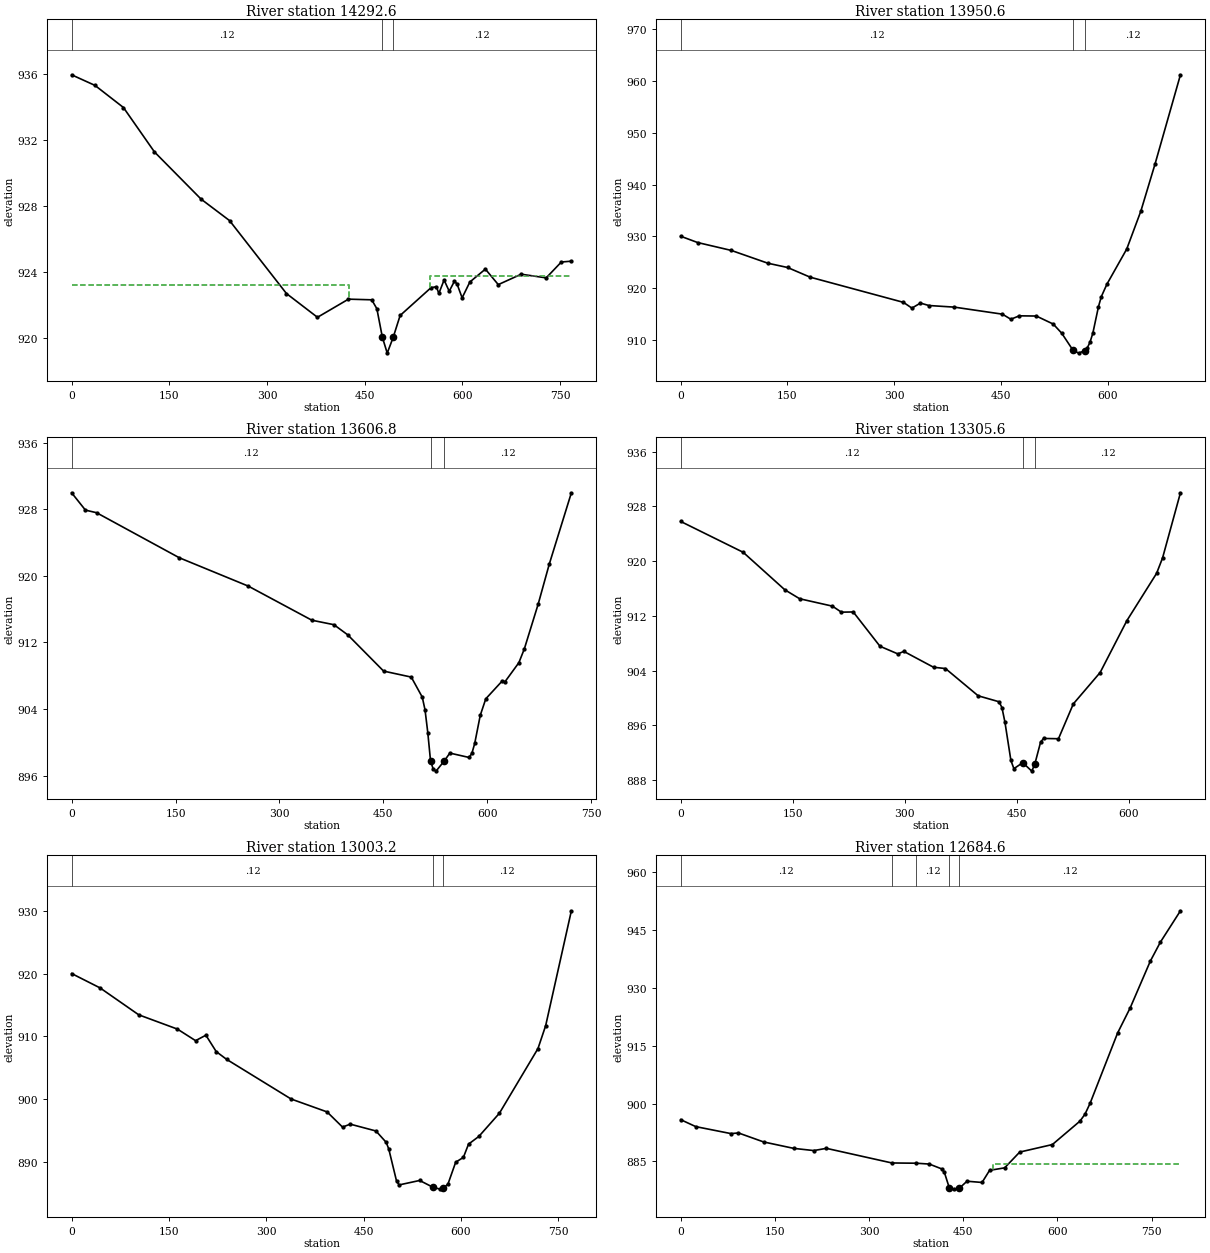
Type RM Length L Ch R = 1 ,14292.6 ,319.8,342,364.3
XS GIS Cut Line= 4
     2306129.794      365343.524     2306479.498       365224.17
     2306527.059      364930.576     2306468.269       364849.34
#Sta/Elev= 30
       0  935.94    35.8   935.3    79.5  933.96   127.1  931.27   198.7  928.41
   242.4  927.11   329.8  922.69   377.4  921.25     425  922.35   460.7  922.31
   468.6  921.77     477  920.05   484.5  919.08  493.63920.0322   504.3  921.36
   551.9  923.05   559.9   923.1   563.8   922.7   571.8  923.51   579.7  922.83
   587.6  923.43   591.6  923.28   599.5  922.43   611.4  923.39   635.2  924.17
     655  923.23   690.1  923.86   728.6  923.64   751.8   924.6   767.2  924.65
#Mann= 3 ,-1 , 0
       0     .12       0     477    .045       0  493.63     .12       0
#XS Ineff= 2 , 0
             426   923.2  550.37          923.74
Permanent Ineff=
       F       F
Bank Sta=477,493.63
XS Rating Curve= 0 ,0
Exp/Cntr=0.3,0.1

Type RM Length L Ch R = 1 ,13950.6 ,341.3,343.8,346.2
XS GIS Cut Line= 3
     2306258.762      365387.351     2306416.879       365384.87
     2306898.685      365131.434
#Sta/Elev= 30
       0  930.01    23.7   928.8    71.2  927.27   122.6   924.8   150.2  923.98
     182  922.11   313.1  917.25     325  916.14     337  917.11   348.9  916.64
   384.6  916.33   452.2  914.97   464.1  913.99     476  914.65   499.9  914.61
   523.7  913.06   535.6   911.3   551.5     908   559.5  907.45   567.8  907.92
   571.4  908.42   575.4  909.56   579.4  911.32   587.3  916.43   591.3  918.36
   599.2  920.77     627  927.54   646.9  934.88   666.8  943.95   702.5  961.17
#Mann= 3 ,-1 , 0
       0     .12       0   551.5    .045       0   567.8     .12       0
Bank Sta=551.5,567.8
XS Rating Curve= 0 ,0
Exp/Cntr=0.3,0.1

Type RM Length L Ch R = 1 ,13606.8 ,301.7,301.2,300.3
XS GIS Cut Line= 2
      2306263.05      365723.508     2306928.114      365444.329
#Sta/Elev= 30
       0     930    19.9  927.92    35.9  927.61   155.4  922.19     255  918.78
   346.7  914.68   378.6  914.14   398.5  912.92   450.3  908.56   490.2  907.84
   506.1  905.43   510.1  903.89   514.1  901.14     518  897.78     522  896.75
     526  896.53     538  897.77   545.9   898.7   573.8  898.17   577.8  898.69
   581.8  899.86   589.8  903.24   597.8  905.23   621.7  907.39   625.6  907.29
   645.6  909.58   653.5  911.25   673.5  916.64   689.4  921.42   721.3     930
#Mann= 3 ,-1 , 0
       0     .12       0     518    .045       0     538     .12       0
Bank Sta=518,538
XS Rating Curve= 0 ,0
Exp/Cntr=0.3,0.1

Type RM Length L Ch R = 1 ,13305.6 ,309.4,302.4,295.2
XS GIS Cut Line= 2
     2306441.528      365943.073     2307062.665      365694.272
#Sta/Elev= 30
       0  925.81    83.6   921.3   139.4  915.81   159.3   914.5   203.1  913.42
   215.1  912.54     231  912.57   266.8  907.55   290.8  906.43   298.7   906.8
   338.5  904.48   354.5  904.29   398.3   900.3   426.2  899.43   430.1  898.58
   434.1  896.46   442.1  890.84   446.1  889.64     458  890.52     470  889.28
     474  890.26   481.9  893.54   485.9  894.06   505.8  894.02   525.7  899.12
   561.6  903.71   597.4   911.3   637.2  918.22   645.2  920.48   669.1     930
#Mann= 3 ,-1 , 0
       0     .12       0     458    .045       0     474     .12       0
Bank Sta=458,474
XS Rating Curve= 0 ,0
Exp/Cntr=0.3,0.1

Type RM Length L Ch R = 1 ,13003.2 ,324.8,318.6,312.3
XS GIS Cut Line= 3
     2306550.113      366190.652     2306885.588      366147.897
     2307217.436      365871.215
#Sta/Elev= 30
       0     920    43.8  917.71   103.4  913.42   163.1  911.14     191   909.3
   206.9  910.17   222.8  907.56   238.7  906.33   338.2     900   393.7  897.94
   417.5  895.52   429.4  895.99     469   894.9   484.8  893.09   488.8  892.02
   500.7  886.94   504.7   886.3   536.4  887.01   557.4   885.9   568.1  885.63
   572.4  885.75     580  886.43   591.9  889.92   603.8  890.69   611.7   892.8
   627.6  894.03   659.3  897.73   718.7  908.03   730.6  911.69   770.2     930
#Mann= 3 ,-1 , 0
       0     .12       0   557.4    .045       0   572.4     .12       0
Bank Sta=557.4,572.4
XS Rating Curve= 0 ,0
Exp/Cntr=0.3,0.1

Type RM Length L Ch R = 1 ,12684.6 ,303.7,307.2,310.8
XS GIS Cut Line= 2
     2306935.751      366595.139     2307410.885      365956.537
#Sta/Elev= 30
       0  895.83      24  894.03      80  892.22      92  892.39     132  890.06
     180  888.39     212  887.82     232   888.4  336.39884.6044   375.4  884.54
     396  884.32     416  883.05     420  882.16     428  878.06     436  877.82
     444  878.08     456  879.87     480  879.55     492  882.69     516  883.34
     540  887.43     592  889.38     636  895.46     644  897.27     652  900.04
     696  918.34     716  924.84     748  936.94     764  941.86     796     950
#Mann= 5 ,-1 , 0
       0     .12       0  336.39    .016       0   375.4     .12       0
     428    .045       0     444     .12       0
#XS Ineff= 2 , 0
                          497.83          884.32
Permanent Ineff=
       F       F
Bank Sta=428,444
XS Rating Curve= 0 ,0
Exp/Cntr=0.3,0.1

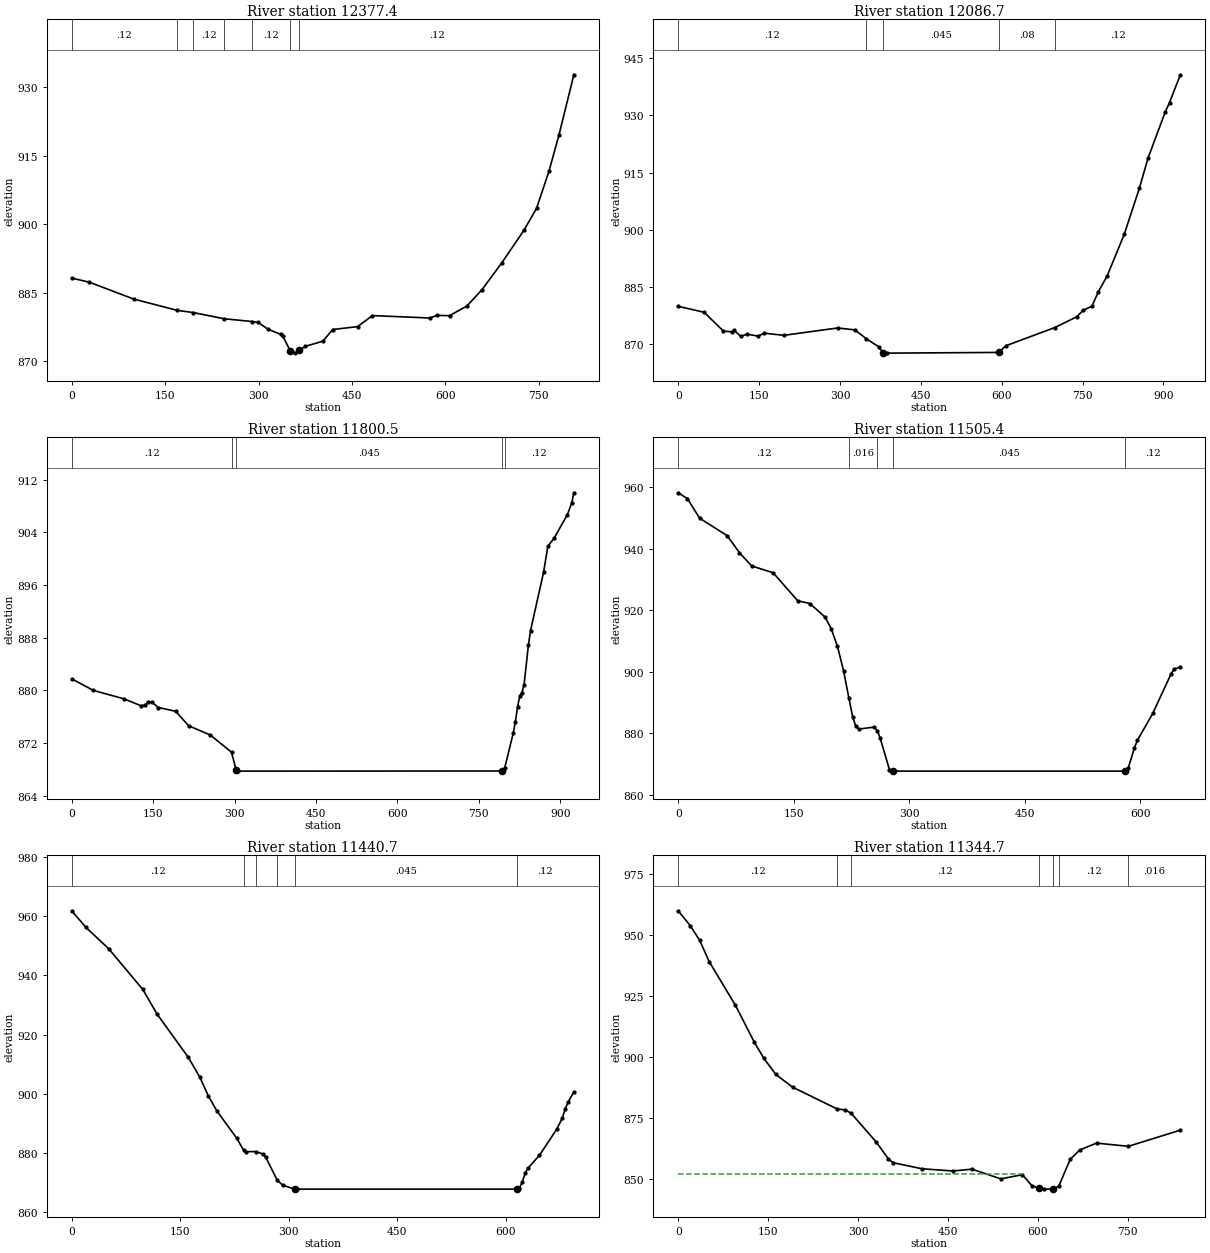
Type RM Length L Ch R = 1 ,12377.4 ,299.5,290.7,281.7
XS GIS Cut Line= 2
     2307087.986      366734.721      2307668.09      366175.054
#Sta/Elev= 30
       0  888.25    27.9  887.37    99.8  883.65  168.97881.2066  194.98880.7095
  244.96879.3493  289.23878.7504   299.3  878.56   315.2  877.04   335.2  875.96
   339.2  875.47   350.5   872.4   359.1  871.83   365.5  872.48   375.1  873.33
     403  874.43     419     877   458.9  877.63   482.8  880.05   574.6  879.52
   586.6  880.09   606.6  880.03   634.5  882.16   658.4  885.68   690.4  891.59
   726.3  898.79   746.2  903.52   766.2  911.66   782.1  919.54   806.1  932.75
#Mann= 7 ,-1 , 0
       0     .12       0  168.97     .06       0  194.98     .12       0
  244.96    .016       0  289.23     .12       0   350.5    .045       0
   365.5     .12       0
Bank Sta=350.5,365.5
XS Rating Curve= 0 ,0
Exp/Cntr=0.3,0.1

Type RM Length L Ch R = 1 ,12086.7 ,289.7,286.2,282.8
XS GIS Cut Line= 2
     2307399.496      367084.497     2307770.849      366230.601
#Sta/Elev= 30
       0     880      48  878.44    83.9   873.5    99.9  873.32   103.9  873.68
   115.9  872.15   127.9  872.71   147.9  872.19   159.8  872.96   195.8   872.4
   295.7  874.33   327.7  873.83  348.49871.5353   371.7  869.41   379.6  867.86
   387.6  867.74  595.19867.9253   607.4  869.66  698.51874.4421   739.3  877.27
   751.3     879   767.3  880.02   779.3  883.86   795.3  887.88   827.2  898.86
   855.2   910.9   871.2  918.77   903.2  930.89   911.2  933.37   931.2  940.63
#Mann= 5 ,-1 , 0
       0     .12       0  348.49     .04       0   379.6    .045       0
  595.19     .08       0  698.51     .12       0
Bank Sta=379.6,595.19
XS Rating Curve= 0 ,0
Exp/Cntr=0.3,0.1

Type RM Length L Ch R = 1 ,11800.5 ,302.3,295.1,287.8
XS GIS Cut Line= 2
     2307699.477      367371.332     2307935.647      366476.907
#Sta/Elev= 30
       0  881.75    39.9  879.99    95.7  878.73   127.6  877.67   135.6  877.78
   139.6  878.22   147.5  878.23   159.5   877.4   191.4  876.83   215.3  874.63
   255.2  873.23  294.31870.6147     303  867.88     307  867.74   793.5  867.76
  797.87868.2869   813.4  873.49   817.4  875.26   821.4  877.49   825.4  879.11
   829.4  879.66   833.4  880.87   841.3  886.83   845.3  889.08   869.3  897.93
   877.2  901.87   889.2  903.18   913.1  906.68   921.1  908.43   925.1     910
#Mann= 5 ,-1 , 0
       0     .12       0  294.31     .04       0     303    .045       0
   793.5     .04       0  797.87     .12       0
Bank Sta=303,793.5
XS Rating Curve= 0 ,0
Exp/Cntr=0.3,0.1

Type RM Length L Ch R = 1 ,11505.4 ,64.9,64.7,64.4
XS GIS Cut Line= 2
     2308203.858      367294.169     2308162.079      366643.446
#Sta/Elev= 30
       0  958.16    11.9  956.28    27.8  949.91    63.6  944.23    79.5   938.7
    95.4   934.4   123.3  932.19   155.1   923.1     171  922.19   190.8  917.76
   198.8  913.95   206.8  908.24   214.7   900.4  221.64891.4651   226.6  885.36
   230.6   882.3   234.6  881.41   254.5  882.04  258.62880.9042   262.4   878.4
   274.3  868.21   278.3  867.74   580.5  867.74   584.5  868.76   592.4  875.26
   596.4  877.77   616.3  886.49   640.1  899.34   644.1  900.84   652.1  901.55
#Mann= 5 ,-1 , 0
       0     .12       0  221.64    .016       0  258.62     .04       0
   278.3    .045       0   580.5     .12       0
Bank Sta=278.3,580.5
XS Rating Curve= 0 ,0
Exp/Cntr=0.3,0.1

Type RM Length L Ch R = 1 ,11440.7 ,95.5,96,96.6
XS GIS Cut Line= 4
      2308228.83      367306.414      2308260.83      367104.624
      2308228.83      366683.455     2308191.215      366627.791
#Sta/Elev= 30
       0  961.85    19.6  956.24    51.1  949.01    98.2  935.25   117.9  926.92
   161.1  912.29   176.8  905.66   188.6  899.35   200.4  894.23   228.2  884.88
  237.48880.8792   240.2  880.41  254.49880.4305   264.1  879.62   268.1  878.52
  284.06870.6927     292     869   307.9  867.79   311.9  867.74   614.7  867.74
   618.7  868.12   622.7  870.14   626.7  873.16   630.6  874.85   646.4  879.19
   670.2  887.98   678.1  891.84     682  894.87     686  897.23   693.9  900.52
#Mann= 6 ,-1 , 0
       0     .12       0  237.48    .016       0  254.49     .06       0
  284.06     .04       0   307.9    .045       0   614.7     .12       0
Bank Sta=307.9,614.7
XS Rating Curve= 0 ,0
Exp/Cntr=0.3,0.1

Type RM Length L Ch R = 1 ,11344.7 ,67.8,66.9,65.6
XS GIS Cut Line= 3
     2308248.114      367307.526     2308350.683      367165.969
     2308316.832      366503.819
#Sta/Elev= 30
       0     960    19.9  953.96    35.8  947.88    51.6   939.2    95.4  921.24
   127.1  906.03     143  899.43   162.9  892.85   190.8  887.64  265.58878.6456
   278.7  878.33  288.65876.9041   330.6  865.06   350.6  858.23   358.5  856.65
   406.5  854.16   458.4  853.24   490.3     854   538.3     850   574.2  851.72
   590.2   847.2   602.2  846.16   610.2   845.8   626.1  845.85     635847.0123
   654.1  858.04   670.1  861.88     698  864.69  751.02863.3651   837.8  869.99
#Mann= 7 ,-1 , 0
       0     .12       0  265.58    .016       0  288.65     .12       0
   602.2    .045       0   626.1     .08       0     635     .12       0
  751.02    .016       0
#XS Ineff= 2 , 0
          574.24  852.18
Permanent Ineff=
       F       F
Bank Sta=602.2,626.1
XS Rating Curve= 0 ,0
Exp/Cntr=0.3,0.1

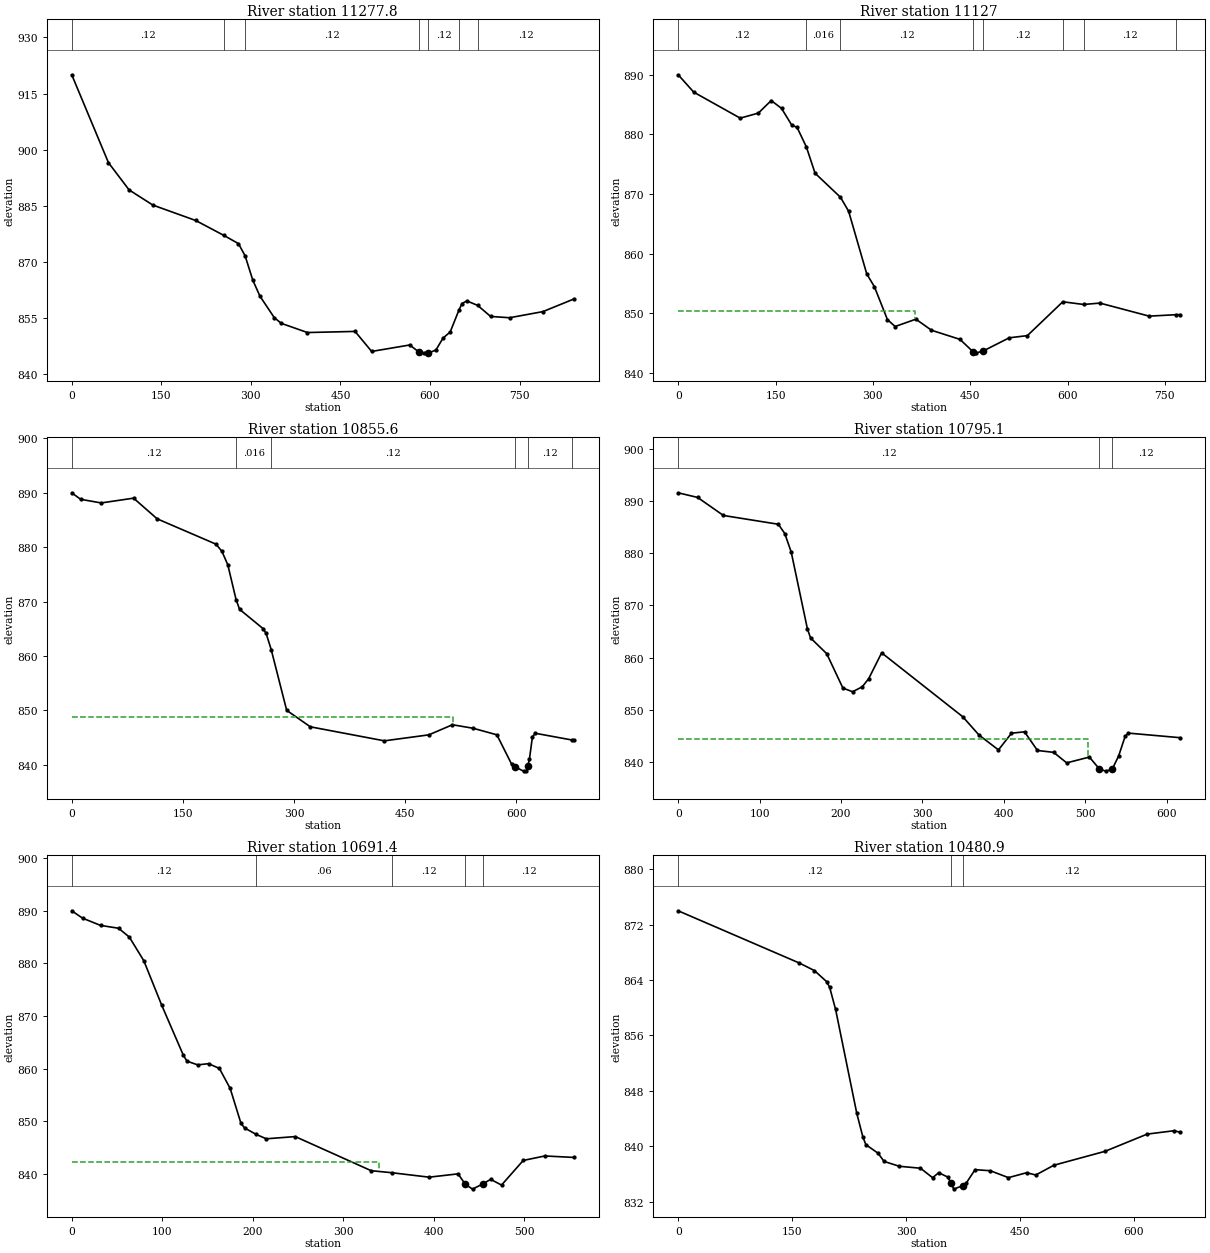
Type RM Length L Ch R = 1 ,11277.8 ,143.1,150.8,158
XS GIS Cut Line= 3
     2308362.106      367314.368     2308418.446      367236.613
     2308378.198      366492.945
#Sta/Elev= 30
       0     920    61.4   896.5      96   889.2   135.8  885.14   207.5  881.02
  254.81877.0159   279.2  874.82  290.33871.5355   303.1  865.07   315.1  860.77
     339  855.04   350.9  853.49   394.7  851.03   474.4  851.33   502.2  845.97
     566   847.7   582.3  845.69   589.9  845.52   597.3  845.54   609.8  846.35
   621.7  849.53   633.7  851.18   648.6857.1275   653.6   858.8   661.6  859.49
  679.75858.2925   701.4  855.34   733.2  854.99     789  856.63   840.8     860
#Mann= 7 ,-1 , 0
       0     .12       0  254.81    .016       0  290.33     .12       0
   582.3    .045       0   597.3     .12       0   648.6    .016       0
  679.75     .12       0
Bank Sta=582.3,597.3
XS Rating Curve= 0 ,0
Exp/Cntr=0.3,0.1

Type RM Length L Ch R = 1 ,11127   ,252.7,271.3,289.7
XS GIS Cut Line= 3
     2308456.114      367277.116     2308484.615      366960.037
     2308596.638      366518.608
#Sta/Elev= 30
       0     890    23.9  887.09    95.5  882.73   123.4  883.57   143.3  885.68
   159.2  884.37   175.1  881.53   183.1  881.19  197.49877.8886   210.9  873.48
  250.07 869.443   262.6   867.1   290.5  856.59   302.4  854.41   322.4  848.91
   334.3  847.75   366.3  848.98   390.3  847.12   434.2  845.59   454.2  843.53
   458.2  843.28     470  843.64   510.1  845.85   538.1  846.22  592.65851.8993
  624.73851.4495   649.9  851.68   725.8  849.49  766.47849.7266   773.8  849.74
#Mann= 8 ,-1 , 0
       0     .12       0  197.49    .016       0  250.07     .12       0
   454.2    .045       0     470     .12       0  592.65    .016       0
  624.73     .12       0  766.47     .06       0
#XS Ineff= 2 , 0
          364.95  850.38
Permanent Ineff=
       F       F
Bank Sta=454.2,470
XS Rating Curve= 0 ,0
Exp/Cntr=0.3,0.1

Type RM Length L Ch R = 1 ,10855.6 ,61.9,60.5,60.4
XS GIS Cut Line= 3
     2308532.027       367268.45     2308516.114      366978.923
     2308839.169      366764.802
#Sta/Elev= 30
       0     890    11.9  888.81    39.7  888.14    83.4  889.02   115.2  885.22
   194.6  880.56   202.6  879.24   210.5  876.78  221.69870.3824   226.4  868.58
   258.2  865.02   262.2  864.16  269.11861.1799     290     850   321.9  846.97
   421.8  844.39   481.8  845.49   513.7  847.35   541.7   846.7   573.6   845.5
   593.6  840.08   597.8  839.63   609.6  838.82   613.6  838.82  615.29839.7621
   617.6  841.05   621.6  845.13   625.6  845.78  675.54844.5286   677.5  844.46
#Mann= 6 ,-1 , 0
       0     .12       0  221.69    .016       0  269.11     .12       0
   597.8    .045       0  615.29     .12       0  675.54    .016       0
#XS Ineff= 2 , 0
          514.34  848.75
Permanent Ineff=
       F       F
Bank Sta=597.8,615.29
XS Rating Curve= 0 ,0
Exp/Cntr=0.3,0.1

Type RM Length L Ch R = 1 ,10795.1 ,106.9,103.7,100.6
XS GIS Cut Line= 3
      2308568.86      367261.663     2308576.878      367011.909
     2308881.617      366807.598
#Sta/Elev= 30
       0  891.53    23.8  890.65    55.5   887.2     123  885.52   130.9  883.74
   138.8   880.2   158.7   865.5   162.6  863.77   182.4  860.77   202.3  854.19
   214.2  853.49   226.1  854.44     234     856   249.9  860.93   349.6   848.7
   369.5  845.21   393.4  842.37   409.4  845.56   425.4  845.83   441.3  842.26
   461.2   841.9   477.2  839.89   505.1     841   517.2  838.75     525  838.31
     533  838.63     541   841.2     549  844.94     553  845.58   616.8   844.7
#Mann= 3 ,-1 , 0
       0     .12       0   517.2    .045       0     533     .12       0
#XS Ineff= 2 , 0
          502.79  844.54
Permanent Ineff=
       F       F
Bank Sta=517.2,533
XS Rating Curve= 0 ,0
Exp/Cntr=0.3,0.1

Type RM Length L Ch R = 1 ,10691.4 ,214.8,210.4,205.2
XS GIS Cut Line= 3
     2308627.014      367304.537     2308661.335      367120.779
     2308934.927      366874.999
#Sta/Elev= 30
       0     890    11.9  888.61    31.8  887.23    51.7  886.69    63.6  885.01
    79.6  880.52    99.4  872.06   123.3  862.56   127.3  861.44   139.2  860.74
   151.1  860.97   163.1  860.06     175  856.27   186.9  849.65   190.9  848.76
  203.74847.5371   214.9   846.7   246.9  847.12   330.8  840.64  353.35840.2609
   394.8  839.41   426.8  840.04   434.8  838.05   442.8  837.14   454.8  838.19
   462.8     839   474.8  837.91   498.8  842.59   522.7  843.44   554.7  843.16
#Mann= 5 ,-1 , 0
       0     .12       0  203.74     .06       0  353.35     .12       0
   434.8    .045       0   454.8     .12       0
#XS Ineff= 2 , 0
          339.32  842.26
Permanent Ineff=
       F       F
Bank Sta=434.8,454.8
XS Rating Curve= 0 ,0
Exp/Cntr=0.3,0.1

Type RM Length L Ch R = 1 ,10480.9 ,239.6,216.3,202.4
XS GIS Cut Line= 4
     2309005.632      367394.657     2308949.073      367158.107
     2309086.527      366971.545     2308968.114      366827.487
#Sta/Elev= 30
       0     874   159.5  866.46   179.4  865.37   195.4  863.78   199.4  862.98
   207.3  859.75   235.2  844.75   243.2  841.34   247.2  840.22   263.2  838.99
   271.2   837.8   291.2   837.1   319.1  836.82   335.1  835.45   343.1  836.17
   355.1  835.54   359.1   834.7   363.1   833.8   375.1  834.32   379.1  834.62
     391  836.61     411  836.46     435  835.46     459  836.17     471  835.84
   494.8  837.25   562.2  839.26   617.8  841.75   653.5  842.24   661.4     842
#Mann= 3 ,-1 , 0
       0     .12       0   359.1    .045       0   375.1     .12       0
Bank Sta=359.1,375.1
XS Rating Curve= 0 ,0
Exp/Cntr=0.3,0.1