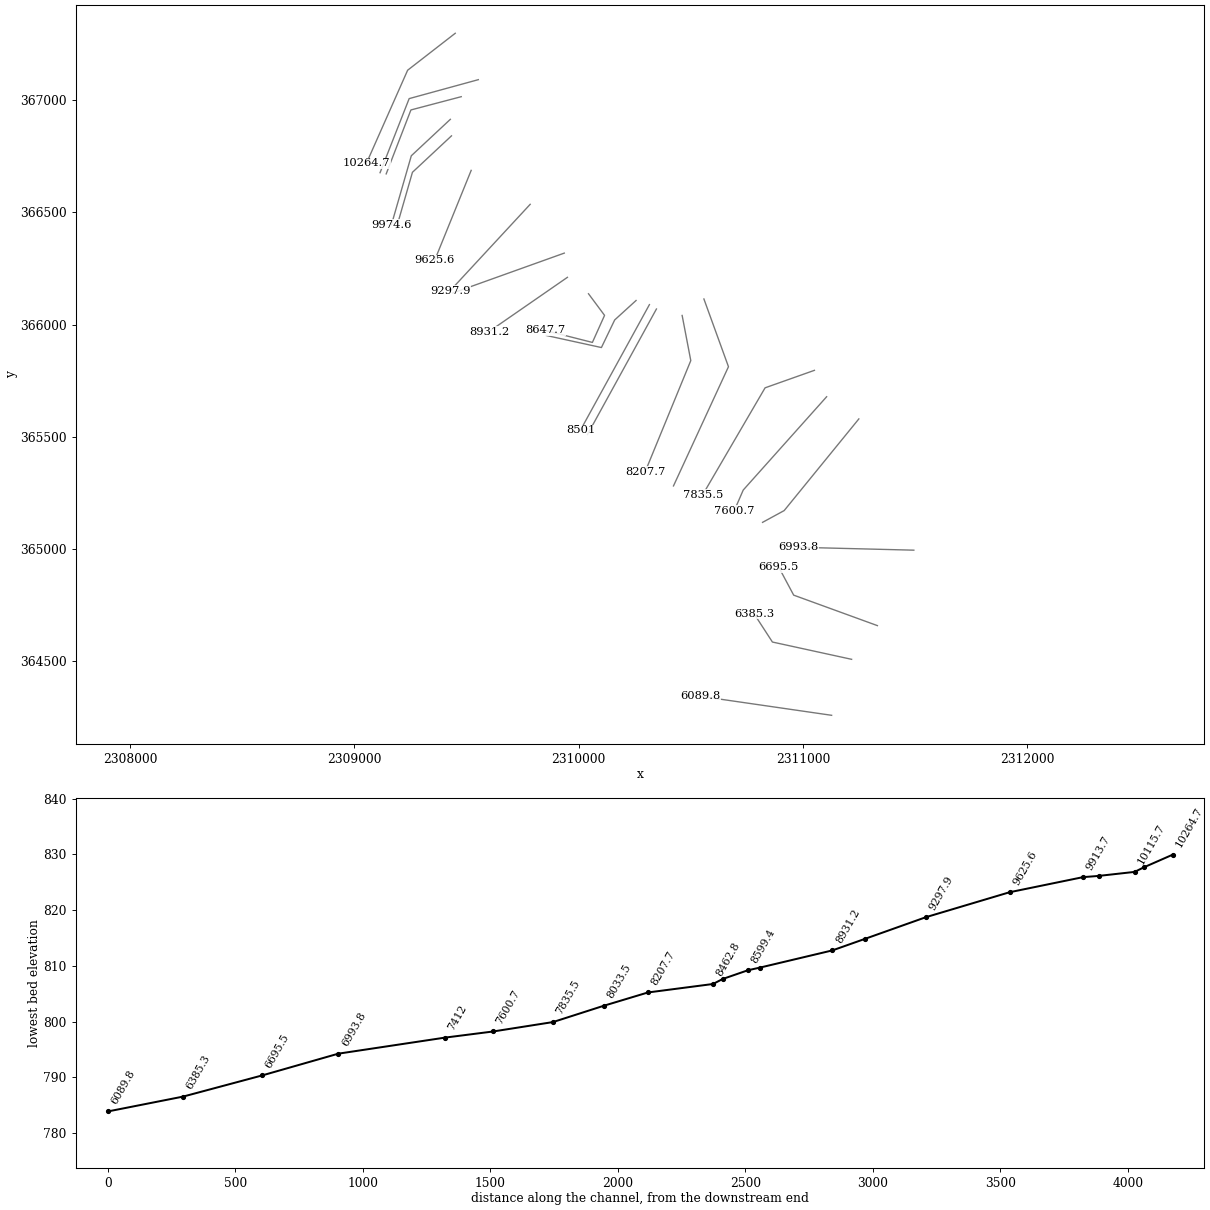
HEC-RAS study SFKINDNCRK.prj: SFKINDNCRK

--- SFKINDNCRK.g01 (geometry) --- (continued)

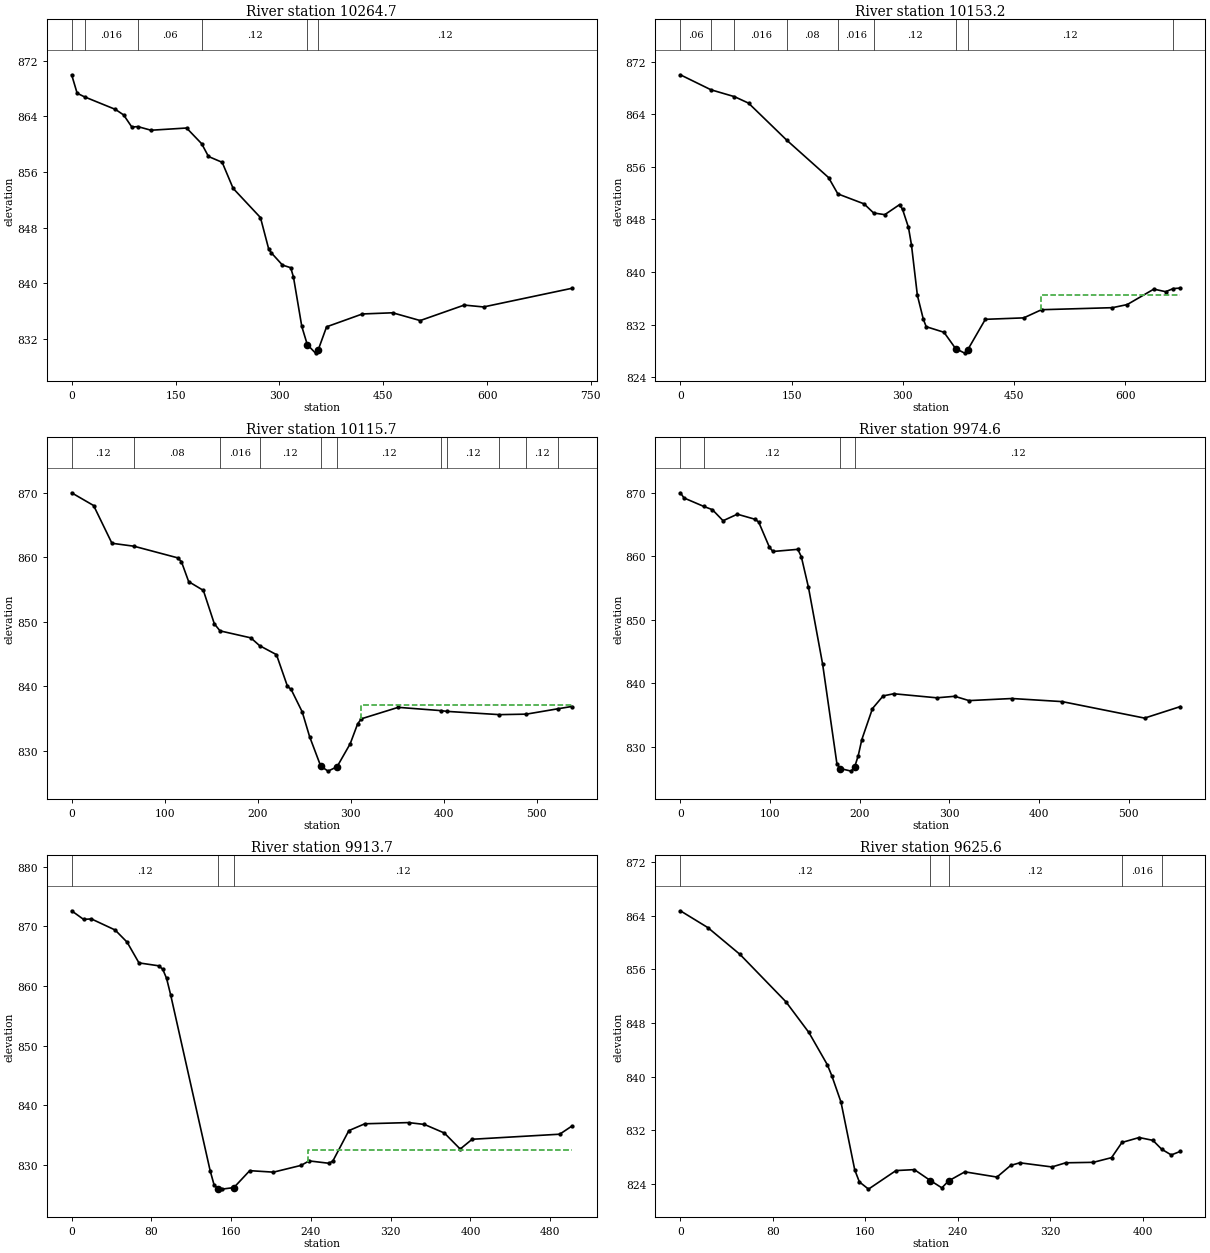
Type RM Length L Ch R = 1 ,10264.7 ,99.7,111.5,106.5
XS GIS Cut Line= 3
        2309450.      367298.652     2309237.726      367133.878
     2309054.081      366719.271
#Sta/Elev= 30
       0     870     7.9  867.35   18.57866.8284    63.2  865.02    75.1  864.22
    86.9  862.48   95.54862.5448   114.6  862.02     166  862.34  187.83860.0727
   197.6  858.24   217.4   857.4   233.2  853.65   272.7  849.44   284.6  844.91
   288.6  844.34   304.5   842.6   316.4  842.22   320.4  840.86   332.4  833.76
   340.3  831.16   352.2  829.92   356.2  830.41   368.2  833.71   419.9  835.56
   463.6  835.73   503.4  834.61     567  836.84   594.9  836.57   722.2  839.25
#Mann= 6 ,-1 , 0
       0     .12       0   18.57    .016       0   95.54     .06       0
  187.83     .12       0   340.3    .045       0   356.2     .12       0
Bank Sta=340.3,356.2
XS Rating Curve= 0 ,0
Exp/Cntr=0.3,0.1

Type RM Length L Ch R = 1 ,10153.2 ,44,37.5,37.5
XS GIS Cut Line= 3
     2309552.848      367091.804     2309244.529       367007.32
     2309114.769       366676.96
#Sta/Elev= 30
       0  869.99   41.25867.7137   72.95866.6691    91.9  865.69   143.6860.0408
   199.8  854.38  212.43851.8875   247.8  850.37  260.63 848.991   275.7  848.73
   295.7  850.26   299.7  849.54   307.7  846.79   311.7  844.16   319.7  836.47
   327.7  832.85   331.6   831.7   355.6  830.85   371.3  828.37   383.5  827.68
   387.5  828.16   411.4  832.82   463.2  833.04   487.2  834.28   582.9  834.59
   602.8  835.06   638.7  837.41   654.7  837.02  664.91837.4947   674.6  837.57
#Mann= 9 ,-1 , 0
       0     .06       0   41.25     .12       0   72.95    .016       0
   143.6     .08       0  212.43    .016       0  260.63     .12       0
   371.3    .045       0   387.5     .12       0  664.91     .06       0
#XS Ineff= 2 , 0
                          486.89          836.47
Permanent Ineff=
       F       F
Bank Sta=371.3,387.5
XS Rating Curve= 0 ,0
Exp/Cntr=0.3,0.1

Type RM Length L Ch R = 1 ,10115.7 ,156.3,141,126.1
XS GIS Cut Line= 3
      2309476.72      367015.931     2309252.357       366956.78
     2309142.112      366671.752
#Sta/Elev= 30
       0  869.99    23.6  868.02    43.3  862.17   67.01861.7106     114  859.91
     118  859.32   125.8  856.22   141.6  854.86   153.4  849.68  159.53 848.587
   192.7   847.5  202.05846.2941   220.2   844.9     232     840     236   839.5
   247.9  836.02   255.8   832.2   267.8  827.61   275.7  826.84  285.36827.5236
   299.5  831.09   307.4  834.14   311.4  834.95   351.1  836.73  397.08836.2216
  403.36 836.105  459.98835.5984  488.87835.6743  522.88836.5088   537.6  836.86
#Mann= 11 ,-1 , 0
       0     .12       0   67.01     .08       0  159.53    .016       0
  202.05     .12       0   267.8    .045       0  285.36     .12       0
  397.08     .06       0  403.36     .12       0  459.98     .06       0
  488.87     .12       0  522.88     .06       0
#XS Ineff= 2 , 0
                          311.46          837.15
Permanent Ineff=
       F       F
Bank Sta=267.8,285.36
XS Rating Curve= 0 ,0
Exp/Cntr=0.3,0.1

Type RM Length L Ch R = 1 ,9974.6  ,61.1,61,61.1
XS GIS Cut Line= 3
     2309428.114      366914.986     2309254.092      366752.481
      2309165.55      366445.189
#Sta/Elev= 30
       0     870       4  869.19   26.07867.8565    35.7  867.34    47.6   865.6
    63.5  866.63    83.3  865.83    87.3   865.4    99.2  861.46   103.2  860.75
     131  861.09   134.9  859.93   142.9  855.08   158.7  842.97   174.6   827.3
   178.6  826.52   190.5  826.12   194.3  826.73   198.4  828.55   202.4  831.09
   214.3  835.99   226.2  837.98   238.1  838.32   286.1  837.68   306.1  837.92
     322  837.24     370  837.57     426  837.08   517.9  834.48   557.9   836.3
#Mann= 4 ,-1 , 0
       0     .08       0   26.07     .12       0   178.6    .045       0
   194.3     .12       0
Bank Sta=178.6,194.3
XS Rating Curve= 0 ,0
Exp/Cntr=0.3,0.1

Type RM Length L Ch R = 1 ,9913.7  ,278.1,288.1,298.1
XS GIS Cut Line= 3
     2309433.162      366841.281     2309259.139      366678.776
     2309186.221      366425.705
#Sta/Elev= 30
       0  872.62    11.9  871.19    19.8  871.26    43.6   869.4    55.6  867.36
    67.5  863.88    87.3  863.39    91.3  862.83    95.2  861.28    99.2  858.57
   138.9  828.99   142.9  826.58   146.8  825.98   150.8   825.9   162.7  826.16
   178.6     829   202.4  828.75   230.2  829.89   238.1  830.64     258  830.24
     262  830.63     278  835.72     294  836.87   337.9  837.07   353.8  836.76
   373.8  835.32   389.7  832.63   401.7  834.27   489.5  835.12   501.5  836.46
#Mann= 3 ,-1 , 0
       0     .12       0   146.8    .045       0   162.7     .12       0
#XS Ineff= 2 , 0
                          236.66          832.39
Permanent Ineff=
       F       F
Bank Sta=146.8,162.7
XS Rating Curve= 0 ,0
Exp/Cntr=0.3,0.1

Type RM Length L Ch R = 1 ,9625.6  ,335.7,327.7,319.6
XS GIS Cut Line= 2
     2309521.019      366687.377     2309358.258      366286.335
#Sta/Elev= 30
       0  864.73    23.8  862.22    51.6  858.22    91.3  851.16   111.2  846.57
   127.1  841.78     131  840.14     139  836.18   150.9  826.06   154.9  824.27
   162.8  823.19   186.6  825.96   202.5   826.1  216.31824.4762   226.3  823.38
  232.12824.4158   246.2  825.77     274  824.99   285.9  826.73   293.8  827.12
   321.6   826.5   333.5  827.12   357.4  827.19   373.2  827.89   382.2830.1575
   397.1  830.89     409  830.47  416.55829.1491   424.9  828.29   432.8  828.83
#Mann= 5 ,-1 , 0
       0     .12       0  216.31    .045       0  232.12     .12       0
   382.2    .016       0  416.55     .12       0
Bank Sta=216.31,232.12
XS Rating Curve= 0 ,0
Exp/Cntr=0.3,0.1

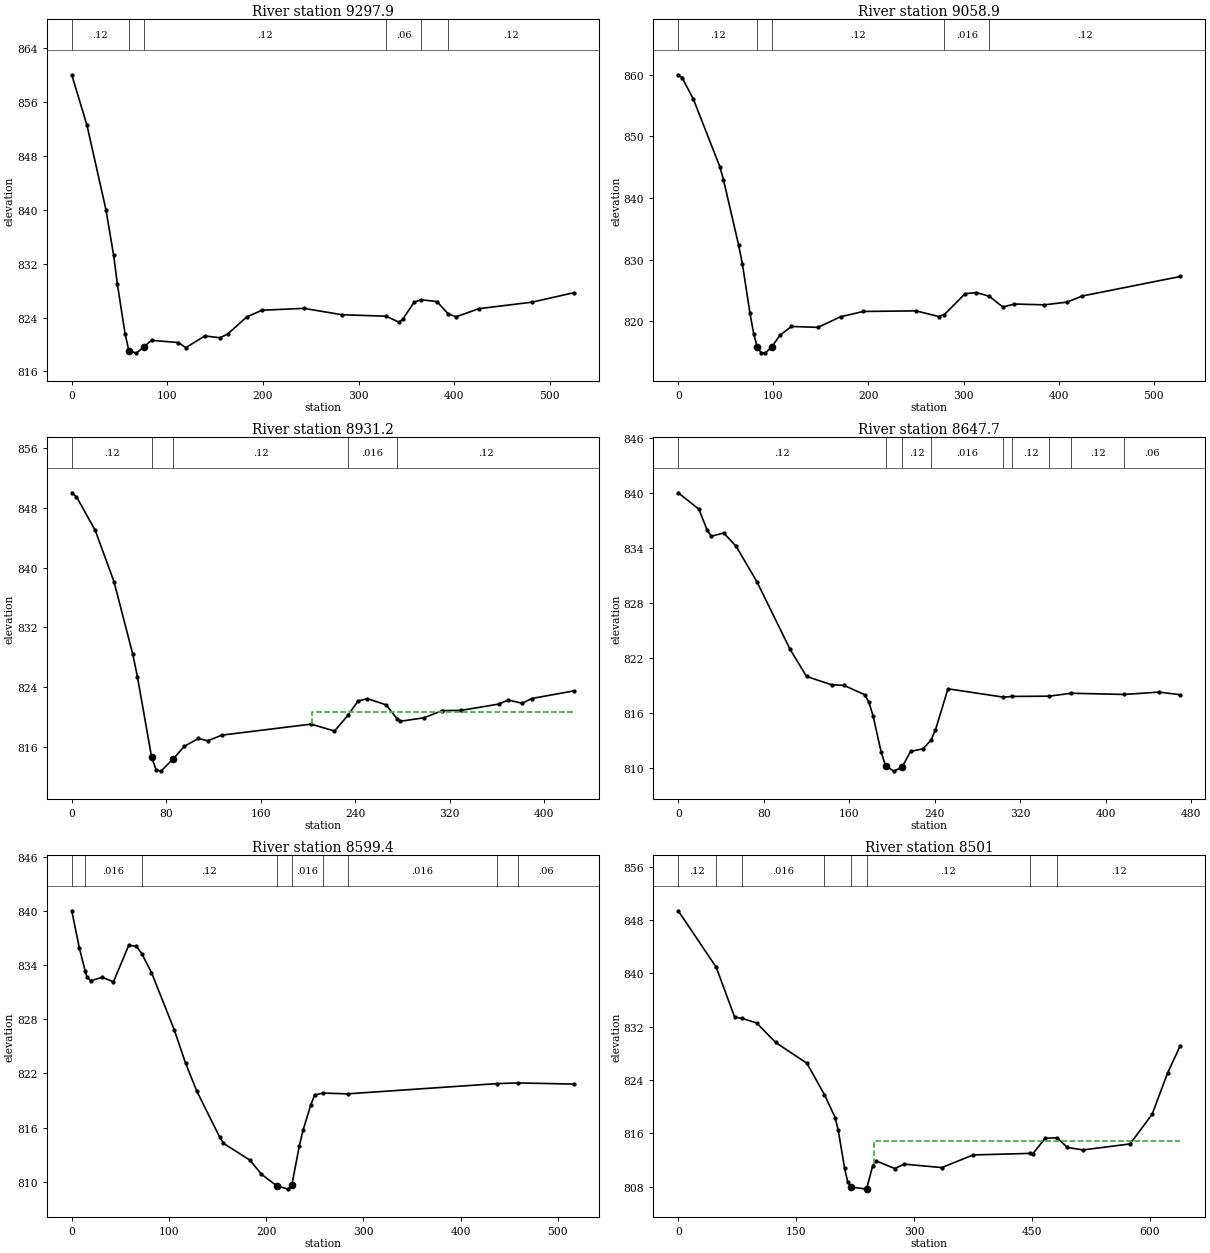
Type RM Length L Ch R = 1 ,9297.9  ,250.2,239,227.7
XS GIS Cut Line= 2
     2309784.114      366536.086     2309427.269      366150.918
#Sta/Elev= 30
       0     860    15.9  852.51    35.8  839.96    43.8  833.22    47.7  828.96
    55.7  821.63    59.7  819.09    67.6  818.72    75.6  819.68    83.5  820.62
   111.4  820.29   119.3  819.53   139.2  821.27   155.1     821   163.1  821.56
     183  824.09   198.9  825.08   242.6  825.36   282.4  824.42  328.85 824.194
   342.1  823.31   346.1  823.73     358  826.26  365.04826.6408   381.9  826.37
   393.3824.5975   401.8   824.1   425.6  825.31   481.3  826.28   525.1  827.68
#Mann= 6 ,-1 , 0
       0     .12       0    59.7    .045       0    75.6     .12       0
  328.85     .06       0  365.04    .016       0   393.3     .12       0
Bank Sta=59.7,75.6
XS Rating Curve= 0 ,0
Exp/Cntr=0.3,0.1

Type RM Length L Ch R = 1 ,9058.9  ,121.8,127.7,133.7
XS GIS Cut Line= 2
     2309936.114       366318.54     2309438.987      366140.502
#Sta/Elev= 30
       0     860       4  859.55    15.9  856.06    43.7  845.11    47.6  842.95
    63.5  832.36    67.5  829.27    75.4  821.35    79.4  817.92    83.1  815.83
    87.4  814.83    91.3  814.84    98.1  815.79   107.2  817.77   119.1  819.16
   146.9  819.01   170.7  820.73   194.5  821.59   250.1  821.69     274  820.77
  279.84821.0825   301.7  824.47   313.6  824.66  327.09 824.061   341.4  822.31
   353.4   822.8   385.1  822.67   408.9  823.11   424.8   824.1     528  827.27
#Mann= 5 ,-1 , 0
       0     .12       0    83.1    .045       0    98.1     .12       0
  279.84    .016       0  327.09     .12       0
Bank Sta=83.1,98.1
XS Rating Curve= 0 ,0
Exp/Cntr=0.3,0.1

Type RM Length L Ch R = 1 ,8931.2  ,271,283.5,295.6
XS GIS Cut Line= 2
     2309950.094      366210.558     2309600.446      365968.627
#Sta/Elev= 30
       0     850       4  849.47    19.9  844.97    35.8  838.09    51.7  828.38
    55.6  825.38    67.6  814.65    71.5  812.91    75.5  812.76      86  814.41
    95.4  816.09   107.3  817.13   115.2  816.82   127.2  817.58   202.7  819.05
   222.5  818.12  233.78820.2078   242.4  822.13   250.3  822.46   266.2  821.63
  275.46819.7656   278.2  819.43     298  819.89   313.9  820.86   329.8  820.89
   361.6  821.73   369.6  822.28   381.5  821.84   389.4  822.47   425.2   823.5
#Mann= 5 ,-1 , 0
       0     .12       0    67.6    .045       0      86     .12       0
  233.78    .016       0  275.46     .12       0
#XS Ineff= 2 , 0
                           203.3          820.61
Permanent Ineff=
       F       F
Bank Sta=67.6,86
XS Rating Curve= 0 ,0
Exp/Cntr=0.3,0.1

Type RM Length L Ch R = 1 ,8647.7  ,48.9,48.2,47.7
XS GIS Cut Line= 4
     2310044.114      366137.286     2310115.687      366040.964
     2310061.422      365920.313     2309850.849      365973.802
#Sta/Elev= 30
       0     840    19.4  838.21    27.1  835.92      31  835.27    42.6  835.63
    54.2  834.17    73.6  830.31   104.5  822.98     120     820   143.4  819.09
     155  819.02   174.5     818   178.4  817.16   182.3  815.66   189.8  811.76
   193.9  810.25   201.7  809.68   209.5  810.13   217.3  811.83     229  812.11
  236.51813.0778   240.6  814.18   252.3  818.65  304.22817.7393  312.03817.8167
  347.03817.8485  367.56818.1638  417.26818.0335   449.8  818.29   469.6     818
#Mann= 9 ,-1 , 0
       0     .12       0   193.9    .045       0   209.5     .12       0
  236.51    .016       0  304.22     .06       0  312.03     .12       0
  347.03     .06       0  367.56     .12       0  417.26     .06       0
Bank Sta=193.9,209.5
XS Rating Curve= 0 ,0
Exp/Cntr=0.3,0.1

Type RM Length L Ch R = 1 ,8599.4  ,99.8,98.5,97.3
XS GIS Cut Line= 4
     2310256.114      366107.253     2310160.843      366020.537
     2310101.689      365897.484     2309856.217      365951.196
#Sta/Elev= 30
       0     840     7.8  835.88   13.81833.3409    15.6  832.68    19.5  832.26
    31.2  832.64    42.9  832.14    58.6  836.18    66.4  836.09   71.97835.2674
      82  833.17   105.4  826.84   117.1  823.14   128.8     820   152.2  814.95
   156.1  814.26   183.4  812.39   195.1  810.84   210.8  809.57   222.4  809.19
   226.4  809.64   234.2  813.99     238  815.73   245.9  818.49   249.8  819.59
  258.27819.8263  283.76819.7385  438.04820.8743  459.33820.9464   516.6  820.82
#Mann= 9 ,-1 , 0
       0     .12       0   13.81    .016       0   71.97     .12       0
   210.8    .045       0   226.4    .016       0  258.27     .12       0
  283.76    .016       0  438.04     .12       0  459.33     .06       0
Bank Sta=210.8,226.4
XS Rating Curve= 0 ,0
Exp/Cntr=0.3,0.1

Type RM Length L Ch R = 1 ,8501    ,38.4,38.2,38
XS GIS Cut Line= 2
     2310315.704      366088.866     2310008.161      365529.094
#Sta/Elev= 30
       0  849.38   48.33 840.911    71.8  833.43   81.71833.2312    99.8  832.55
   123.8  829.64   163.7  826.51  185.87821.8236   199.6  818.37   203.6  816.44
   211.6  810.78   215.6  808.68   219.6  807.95   239.5  807.63   247.5  811.17
   251.5  811.87   275.4  810.72   287.4  811.38   335.3  810.86   375.2  812.76
  447.73812.9905   451.1  812.94     467  815.29  482.26815.3078     495  813.88
     515  813.51   574.8  814.41   602.8  818.85   622.7   825.1   638.7  829.15
#Mann= 8 ,-1 , 0
       0     .12       0   48.33     .08       0   81.71    .016       0
  185.87     .12       0   219.6    .045       0   239.5     .12       0
  447.73    .016       0  482.26     .12       0
#XS Ineff= 2 , 0
                          249.23          814.78
Permanent Ineff=
       F       F
Bank Sta=219.6,239.5
XS Rating Curve= 0 ,0
Exp/Cntr=0.3,0.1

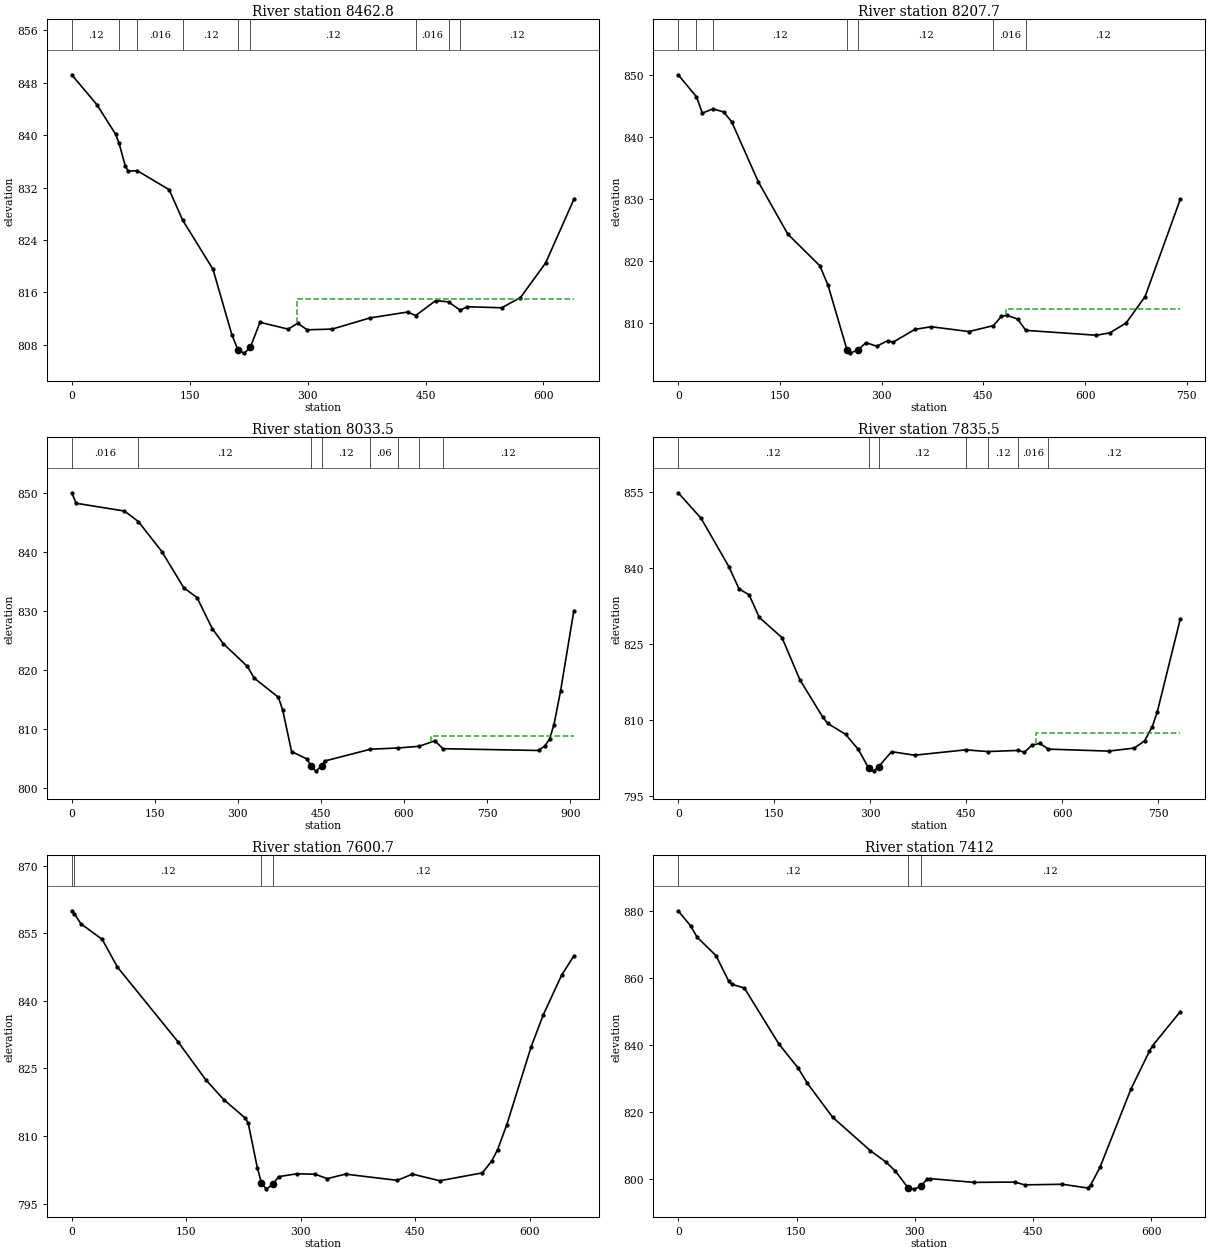
Type RM Length L Ch R = 1 ,8462.8  ,252.2,255,257.8
XS GIS Cut Line= 2
     2310346.954      366069.335     2310039.411      365509.562
#Sta/Elev= 30
       0   849.2    31.9  844.66    55.9  840.11   60.22838.7496    67.9  835.35
    71.8  834.48   83.06834.5845   123.8  831.68  141.22 826.996   179.6  819.54
   203.6  809.56   211.6  807.15   219.6  806.73   227.1  807.63   239.5  811.43
   275.4  810.39   287.4   811.3   299.4  810.29   331.3   810.4   379.2   812.1
   427.1     813  437.55812.4662     463  814.75  479.29814.5448  494.14 813.288
     503  813.81   546.9  813.65   570.8  815.21   602.8  820.49   638.7  830.19
#Mann= 9 ,-1 , 0
       0     .12       0   60.22     .08       0   83.06    .016       0
  141.22     .12       0   211.6    .045       0   227.1     .12       0
  437.55    .016       0  479.29     .06       0  494.14     .12       0
#XS Ineff= 2 , 0
                          286.79          814.95
Permanent Ineff=
       F       F
Bank Sta=211.6,227.1
XS Rating Curve= 0 ,0
Exp/Cntr=0.3,0.1

Type RM Length L Ch R = 1 ,8207.7  ,175.4,174.2,172.9
XS GIS Cut Line= 3
     2310461.579      366040.537     2310500.114      365839.282
      2310296.75      365343.901
#Sta/Elev= 30
       0     850   26.93846.4638    35.5  843.84   51.44844.5234      67  844.02
    78.8  842.45   118.2  832.75   161.6  824.36   208.9  819.26   220.9  816.13
   248.9  805.73   252.9  805.21   264.9   805.7   276.8   806.9   292.8  806.32
   308.8  807.22   316.8  806.96   348.8  809.02   372.8  809.46   428.7  808.68
  464.85 809.642   476.7  811.14   484.6  811.31   500.6  810.68  512.58808.8729
   616.5  808.09   636.5  808.47   660.5  810.06   688.5  814.32   740.4  829.99
#Mann= 7 ,-1 , 0
       0     .12       0   26.93    .016       0   51.44     .12       0
   248.9    .045       0   264.9     .12       0  464.85    .016       0
  512.58     .12       0
#XS Ineff= 2 , 0
                           483.8          812.25
Permanent Ineff=
       F       F
Bank Sta=248.9,264.9
XS Rating Curve= 0 ,0
Exp/Cntr=0.3,0.1

Type RM Length L Ch R = 1 ,8033.5  ,201.1,198.1,195
XS GIS Cut Line= 3
     2310558.605      366114.046     2310668.114      365812.041
     2310422.941      365280.537
#Sta/Elev= 30
       0  849.99     7.9  848.22    95.2   846.9   120.3 845.116   162.6  840.04
   202.3  833.89   226.1  832.24   253.8  826.95   273.6  824.42   317.3  820.55
   329.2   818.6     373  815.34     381  813.12   396.9  806.13   424.8  804.86
   432.7  803.62   440.7  802.81   451.1  803.66   456.6  804.52  539.41806.5238
  589.49  806.74  627.11807.0177   655.7  807.95  670.18 806.613   842.9  806.31
   854.8  807.13   862.8  808.27   870.7   810.7   882.7  816.43   906.6     830
#Mann= 8 ,-1 , 0
       0    .016       0   120.3     .12       0   432.7    .045       0
   451.1     .12       0  539.41     .06       0  589.49     .12       0
  627.11    .016       0  670.18     .12       0
#XS Ineff= 2 , 0
                          649.12          808.78
Permanent Ineff=
       F       F
Bank Sta=432.7,451.1
XS Rating Curve= 0 ,0
Exp/Cntr=0.3,0.1

Type RM Length L Ch R = 1 ,7835.5  ,238.4,234.8,230.9
XS GIS Cut Line= 3
     2311051.265      365795.897     2310831.355      365717.914
     2310553.808      365242.231
#Sta/Elev= 30
       0  854.93    35.6  849.91    79.1  840.33    94.9  835.95   110.7  834.75
   126.6  830.29   162.1  826.29   189.8  818.01   225.4  810.64   233.3  809.34
   261.3  807.18   281.2  804.19   297.2  800.55   305.2   799.9   313.1  800.79
   333.1  803.75     369  803.05   449.1804.1105  483.11803.7685  531.13803.9945
   540.6  803.64   552.6  805.06   564.6  805.38  578.22804.2484   672.3  803.86
   712.2  804.46   728.2  805.87   740.2  808.65   748.1  811.61   784.1     830
#Mann= 7 ,-1 , 0
       0     .12       0   297.2    .045       0   313.1     .12       0
   449.1     .06       0  483.11     .12       0  531.13    .016       0
  578.22     .12       0
#XS Ineff= 2 , 0
                          558.93           807.5
Permanent Ineff=
       F       F
Bank Sta=297.2,313.1
XS Rating Curve= 0 ,0
Exp/Cntr=0.3,0.1

Type RM Length L Ch R = 1 ,7600.7  ,187.8,188.7,189.6
XS GIS Cut Line= 3
     2311105.767      365678.189     2310733.911      365262.175
     2310694.086      365170.509
#Sta/Elev= 30
       0     860    3.33859.3673      12  857.11    39.9  853.66    59.8  847.52
   139.5  830.86   175.4  822.54   199.3  818.06   227.2  814.01   231.2  812.87
   243.1  802.98   248.5  799.58   255.1  798.21   263.5  799.29     271  800.98
   294.9  801.61   318.8  801.52   334.8  800.54   358.7  801.54   426.5  800.16
   446.4  801.54   482.3  800.07     538  801.82     550  804.37     558  806.98
     570  812.49     602  829.84     618  836.97   641.9  845.71   657.9     850
#Mann= 4 ,-1 , 0
       0     .08       0    3.33     .12       0   248.5    .045       0
   263.5     .12       0
Bank Sta=248.5,263.5
XS Rating Curve= 0 ,0
Exp/Cntr=0.3,0.1

Type RM Length L Ch R = 1 ,7412    ,439.4,418.2,397
XS GIS Cut Line= 3
     2311249.364      365579.287     2310916.448      365170.612
     2310820.114      365118.148
#Sta/Elev= 30
       0  880.01      16  875.43      24  872.14    47.9  866.66    63.9  859.12
    67.9  858.14    83.9     857   127.8  840.29   151.7   833.3   163.7  828.67
   195.7  818.56   243.6  808.57   263.6  805.15   275.5  802.46   291.5   797.5
   299.5  797.11   307.3  797.96   315.5  799.98   319.5  800.24   375.4  799.12
   427.3  799.21   439.3  798.38   487.2  798.56   519.1  797.45   523.1  798.31
     535  803.65   574.1  826.88   597.6  838.18   601.6  839.84   636.8     850
#Mann= 3 ,-1 , 0
       0     .12       0   291.5    .045       0   307.3     .12       0
Bank Sta=291.5,307.3
XS Rating Curve= 0 ,0
Exp/Cntr=0.3,0.1

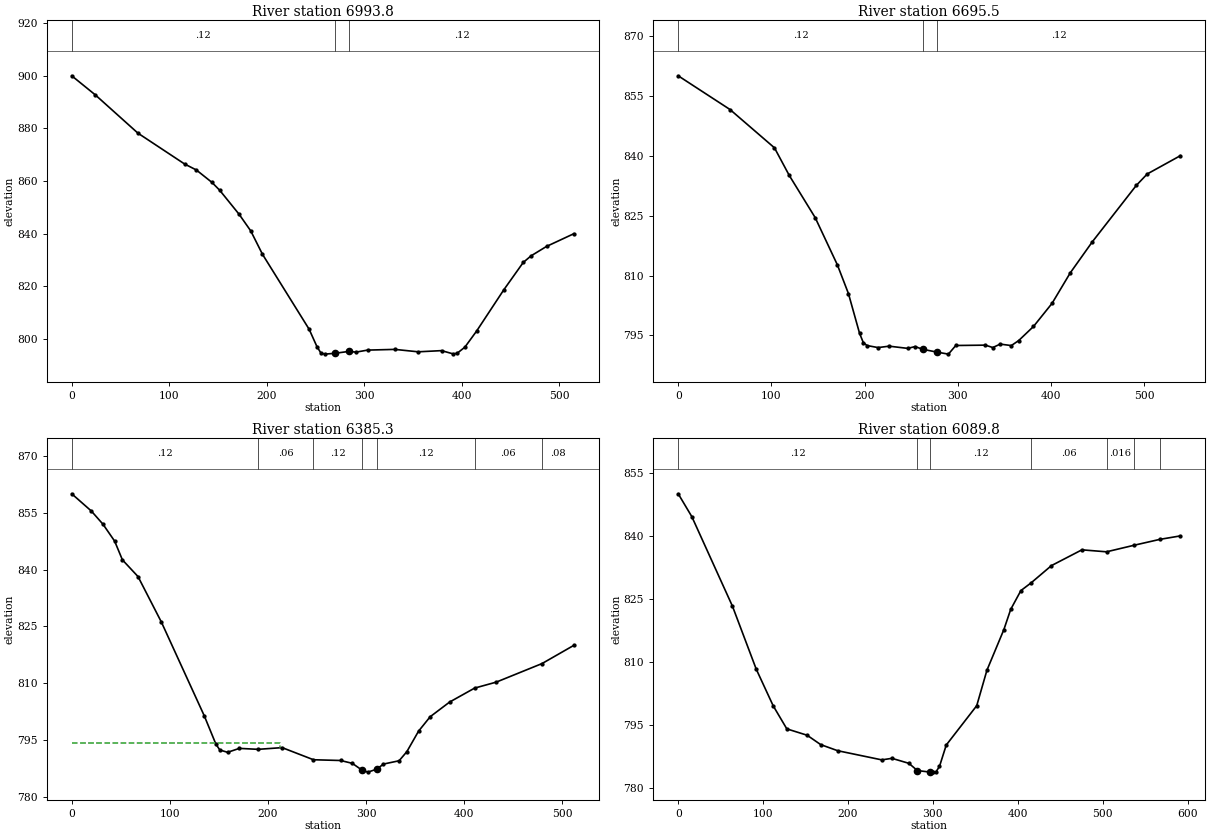
Type RM Length L Ch R = 1 ,6993.8  ,305.6,298.3,291
XS GIS Cut Line= 2
     2311494.535      364994.116     2310979.702      365007.032
#Sta/Elev= 30
       0  900.01      24  892.81    67.9  878.21   115.8  866.48   127.8  864.22
   143.7  859.53   151.7  856.53   171.7  847.36   183.6  841.06   195.6  832.19
   243.5  803.67   251.5  797.07   255.5  794.68   259.5  794.23   269.6  794.53
   284.6  795.28   291.4  794.98   303.4  795.76   331.4  796.03   355.3  795.11
   379.3  795.56   391.2  794.32   395.2  794.53   403.2  796.87   415.2  802.96
   443.1  818.65   463.1  829.08   471.1  831.58     487  835.17     515     840
#Mann= 3 ,-1 , 0
       0     .12       0   269.6    .045       0   284.6     .12       0
Bank Sta=269.6,284.6
XS Rating Curve= 0 ,0
Exp/Cntr=0.3,0.1

Type RM Length L Ch R = 1 ,6695.5  ,306.1,310.2,313.2
XS GIS Cut Line= 3
     2311332.114       364657.73     2310958.856      364793.616
     2310892.114      364918.545
#Sta/Elev= 30
       0     860    55.6  851.56   103.3  841.97   119.2  835.05     147   824.5
   170.8  812.68   182.7  805.48   194.6  795.56   198.6  793.24   202.6  792.48
   214.5  791.97   226.4  792.32   246.3  791.77   254.2  792.22   262.6  791.53
   277.6  790.84     290  790.33   297.9  792.49   329.7  792.58   337.6  791.98
   345.6  792.84   357.5  792.47   365.4  793.72   381.3  797.25   401.2  803.03
   420.8  810.68   444.4  818.43   491.6  832.55   503.4  835.43   538.9     840
#Mann= 3 ,-1 , 0
       0     .12       0   262.6    .045       0   277.6     .12       0
Bank Sta=262.6,277.6
XS Rating Curve= 0 ,0
Exp/Cntr=0.3,0.1

Type RM Length L Ch R = 1 ,6385.3  ,295,295.5,297.3
XS GIS Cut Line= 3
     2311217.152      364507.499     2310864.087      364584.565
     2310782.197      364710.621
#Sta/Elev= 30
       0     860    19.9  855.47    31.8  851.98    43.7  847.51    51.6  842.57
    67.5  838.16    91.3  826.16     135  801.42   146.9  793.91   150.9  792.38
   158.8  791.76   170.8   792.8  189.91792.5466   214.4     793  246.36789.7976
     274   789.6   285.9  788.85   295.8  787.06   301.8  786.53   310.8  787.31
   317.7  788.66   333.6  789.53   341.5  791.93   353.4  797.33   365.3  801.16
   385.1  805.03  410.57808.7126   432.6  810.29  479.28  815.19   511.7     820
#Mann= 7 ,-1 , 0
       0     .12       0  189.91     .06       0  246.36     .12       0
   295.8    .045       0   310.8     .12       0  410.57     .06       0
  479.28     .08       0
#XS Ineff= 2 , 0
          212.38  794.19
Permanent Ineff=
       F       F
Bank Sta=295.8,310.8
XS Rating Curve= 0 ,0
Exp/Cntr=0.3,0.1

Type RM Length L Ch R = 1 ,6089.8  ,207.3,206.8,206.2
XS GIS Cut Line= 2
     2311128.046      364257.888     2310542.763      364342.698
#Sta/Elev= 30
       0     850      16  844.58    63.9  823.28    91.9  808.32   111.9   799.6
   127.9  794.14   151.8  792.63   167.8   790.4   187.8  788.95   239.8  786.77
   251.7  787.14   271.7  785.95   281.7  784.23   296.7  783.87   299.7  783.86
   303.7  783.96   307.7   785.2   315.7   790.3   351.6  799.65   363.6  808.07
   383.6  817.75   391.6  822.53   403.6     827  415.73828.8514   439.6  832.94
   475.5  836.69  504.48836.2192  537.42 837.801  567.18839.1718   591.4     840
#Mann= 7 ,-1 , 0
       0     .12       0   281.7    .045       0   296.7     .12       0
  415.73     .06       0  504.48    .016       0  537.42     .08       0
  567.18     .06       0
Bank Sta=281.7,296.7
XS Rating Curve= 0 ,0
Exp/Cntr=0.3,0.1