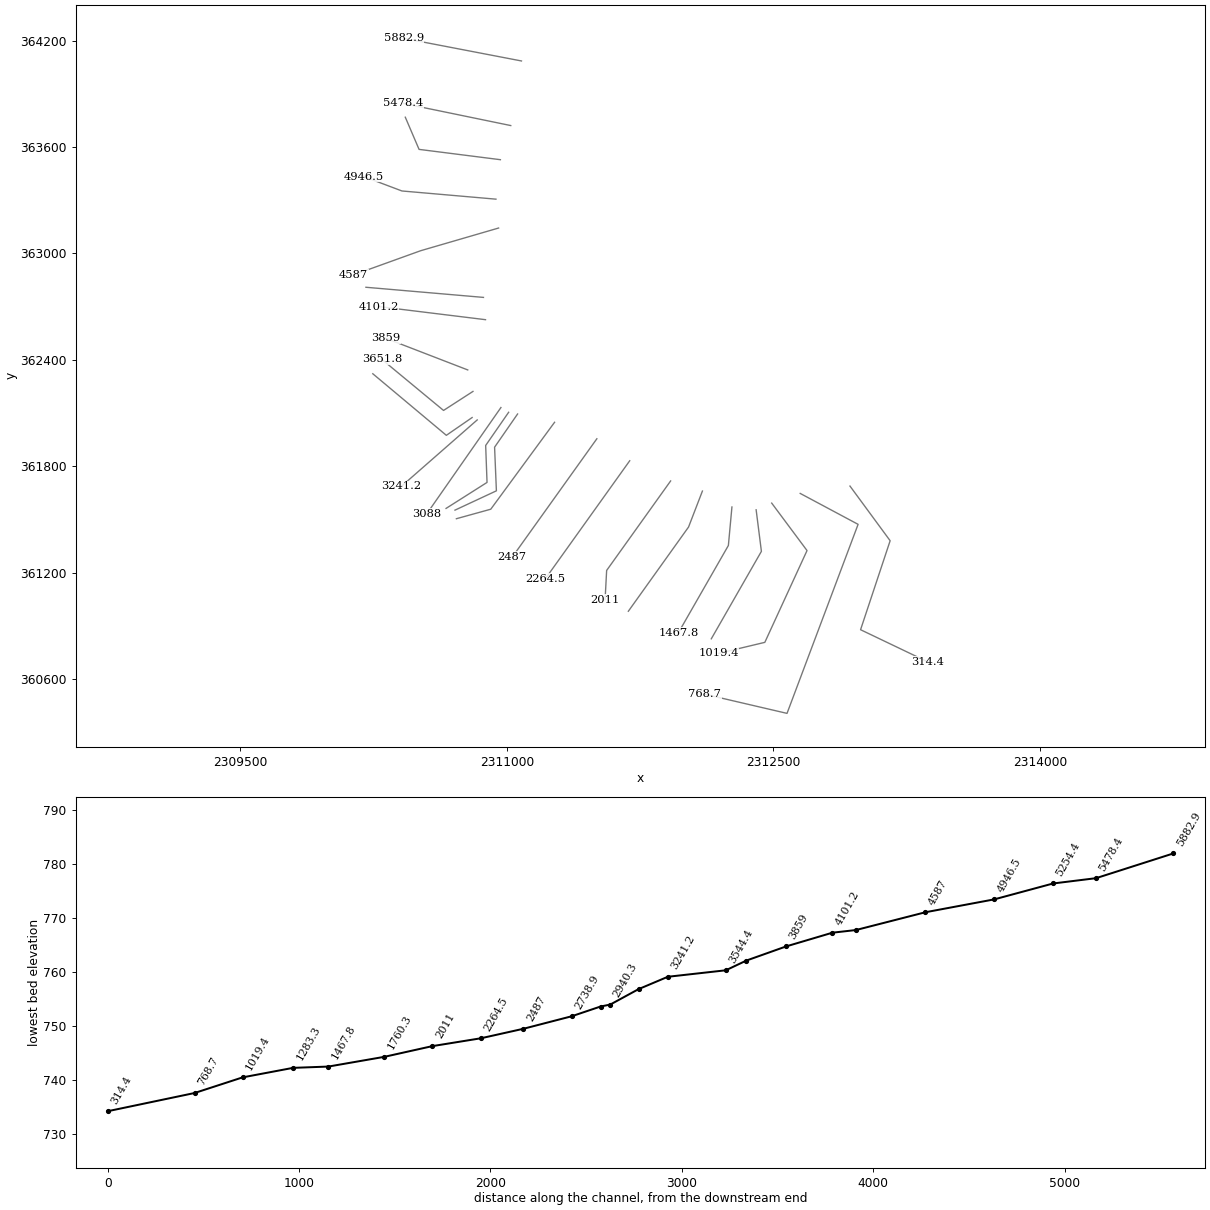
HEC-RAS study SFKINDNCRK.prj: SFKINDNCRK

--- SFKINDNCRK.g01 (geometry) --- (continued)

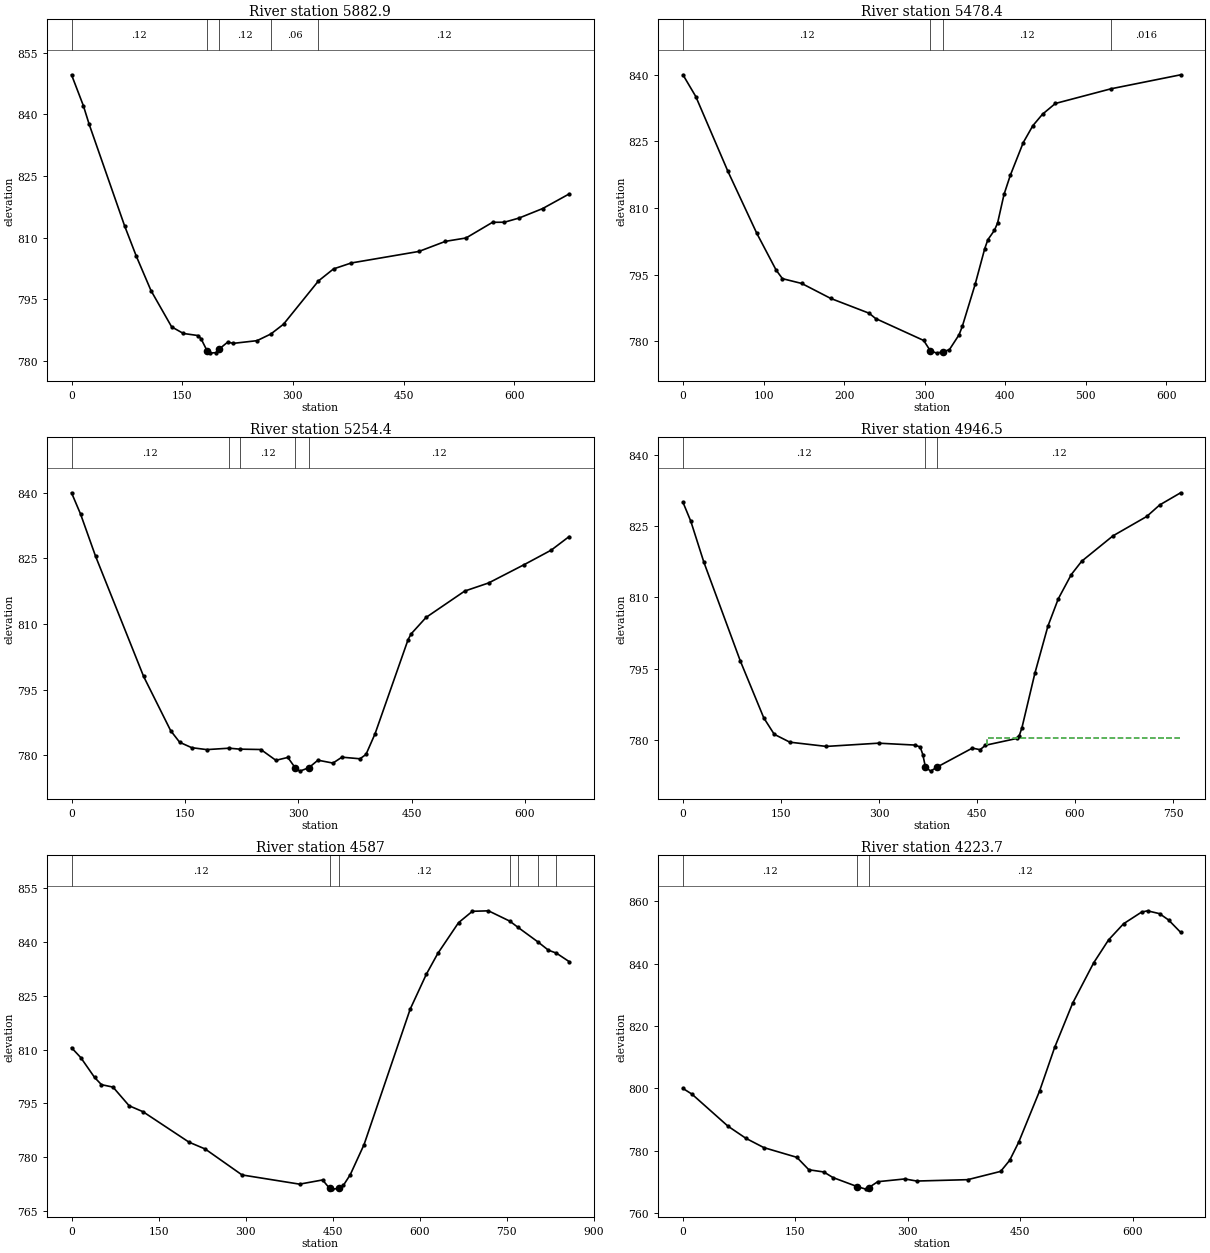
Type RM Length L Ch R = 1 ,5882.9  ,405.1,404.6,404
XS GIS Cut Line= 2
     2311082.374      364084.763     2310420.179      364212.312
#Sta/Elev= 30
       0  849.61      16  842.12    23.9  837.57    71.8  812.94    87.8   805.5
   107.7  797.14   135.7  788.32   151.6  786.72   171.6  786.21   175.6  785.41
   183.6  782.55   187.6  781.94   195.5  782.06   199.5  782.84   211.5   784.6
   219.5  784.32   251.4  784.97  270.15786.5925   287.3  788.97  334.65799.4935
   355.1  802.42   379.1  803.86   470.9  806.67   506.8  809.12   534.7  809.94
   570.6  813.75   586.6  813.77   606.5  814.78   638.4  817.08   674.4  820.64
#Mann= 5 ,-1 , 0
       0     .12       0   183.6    .045       0   199.5     .12       0
  270.15     .06       0  334.65     .12       0
Bank Sta=183.6,199.5
XS Rating Curve= 0 ,0
Exp/Cntr=0.3,0.1

Type RM Length L Ch R = 1 ,5478.4  ,222.2,224,225.8
XS GIS Cut Line= 2
     2311022.005      363720.659     2310417.164      363845.587
#Sta/Elev= 30
       0     840    15.9  835.12    55.8  818.27    91.6  804.34   115.6  796.06
   123.5  794.12   147.4  793.04   183.3  789.68   231.1  786.34   239.1  785.15
   298.8  780.21   306.8  777.95   314.8  777.36   322.8  777.67   330.7  778.14
   342.7  781.49   346.7  783.37   362.6  792.81   374.6   800.9   378.5  802.91
   386.5  804.97   390.5  806.64   398.5  813.08   406.4  817.43   422.4  824.76
   434.3  828.56   446.3  831.14   462.2  833.55  531.36836.8597   617.6     840
#Mann= 4 ,-1 , 0
       0     .12       0   306.8    .045       0   322.8     .12       0
  531.36    .016       0
Bank Sta=306.8,322.8
XS Rating Curve= 0 ,0
Exp/Cntr=0.3,0.1

Type RM Length L Ch R = 1 ,5254.4  ,304.6,307.9,310.2
XS GIS Cut Line= 3
     2310963.819      363528.243     2310506.312      363586.364
     2310428.923      363767.729
#Sta/Elev= 30
       0  839.99    11.9  835.15    31.8  825.49    95.4  798.01   131.2  785.62
   143.1  782.97     159  781.74   178.9   781.3  208.61781.6225  222.45781.4066
   250.5  781.32   270.4  778.85   286.2  779.51  296.16777.0839   302.2  776.38
   314.1  777.17     326  778.88   345.9  778.22   357.8  779.57   381.7   779.2
   389.6  780.19   401.6  784.91   445.3  806.43   449.3  807.74   469.1  811.51
   520.3  817.54   551.9  819.39   599.2   823.6   634.7  826.89   658.4  829.99
#Mann= 5 ,-1 , 0
       0     .12       0  208.61     .06       0  222.45     .12       0
  296.16    .045       0   314.1     .12       0
Bank Sta=296.16,314.1
XS Rating Curve= 0 ,0
Exp/Cntr=0.3,0.1

Type RM Length L Ch R = 1 ,4946.5  ,352.1,359.5,368.2
XS GIS Cut Line= 3
     2310938.878      363305.773     2310410.156      363351.921
     2310194.196       363433.47
#Sta/Elev= 30
       0     830      12  826.01    31.9  817.43    87.8  796.61   123.7  784.64
   139.7  781.19   163.6  779.53   219.5  778.64   299.3  779.32   355.2  778.92
   363.1  778.52   367.1  776.93   371.1  774.31   379.1  773.44   389.3  774.32
   442.9  778.28   454.9  777.95   462.9  778.88   510.8  780.31   514.8  780.93
   518.8  782.54   538.7  794.06   558.6  803.94   574.5   809.7   594.4   814.8
   610.3   817.6   658.1  822.93   709.8  827.01   729.7  829.44   761.6  831.99
#Mann= 3 ,-1 , 0
       0     .12       0   371.1    .045       0   389.3     .12       0
#XS Ineff= 2 , 0
                          464.81          780.41
Permanent Ineff=
       F       F
Bank Sta=371.1,389.3
XS Rating Curve= 0 ,0
Exp/Cntr=0.3,0.1

Type RM Length L Ch R = 1 ,4587    ,371.8,363.3,363.7
XS GIS Cut Line= 3
     2310953.707      363143.064     2310515.308       363015.16
     2310137.982      362878.903
#Sta/Elev= 30
       0  810.53    15.9  807.78    39.7  802.24    51.6  800.22    71.5  799.54
    99.3  794.33   123.1  792.68   202.5  784.17   230.3  782.27   293.9  775.02
   393.1  772.45   432.8  773.62   444.8  771.28   448.7  771.06   460.6  771.24
   468.6   772.1   480.5  775.09   504.3   783.5   583.8   821.3   611.6  831.03
   631.4  836.85   667.2  845.45     691  848.62   718.8  848.75   755.5845.8742
  769.71844.1365  804.15840.0565   822.1  837.76  835.72836.9539   857.8  834.58
#Mann= 7 ,-1 , 0
       0     .12       0   444.8    .045       0   460.6     .12       0
   755.5     .06       0  769.71     .12       0  804.15    .016       0
  835.72     .12       0
Bank Sta=444.8,460.6
XS Rating Curve= 0 ,0
Exp/Cntr=0.3,0.1

Type RM Length L Ch R = 1 ,4223.7  ,124,122.6,120.9
XS GIS Cut Line= 2
     2310868.604      362752.046     2310207.476      362809.176
#Sta/Elev= 30
       0     800      12  798.18      60  787.93      84  784.03   107.9  781.06
   151.9  777.95   167.9  773.97   187.9  773.26   199.9  771.49   232.6  768.56
   243.8  767.77   247.6  768.23   259.8  770.15   295.8  771.03   311.8  770.36
   379.8   770.8   423.7  773.45   435.7  776.98   447.7  782.77   475.7  799.24
   495.7  813.13   519.7   827.3   547.7   840.2   567.6  847.56   587.6  852.73
   611.6  856.46   619.6  856.87   635.6  855.96   647.6  853.95   663.6  850.01
#Mann= 3 ,-1 , 0
       0     .12       0   232.6    .045       0   247.6     .12       0
Bank Sta=232.6,247.6
XS Rating Curve= 0 ,0
Exp/Cntr=0.3,0.1

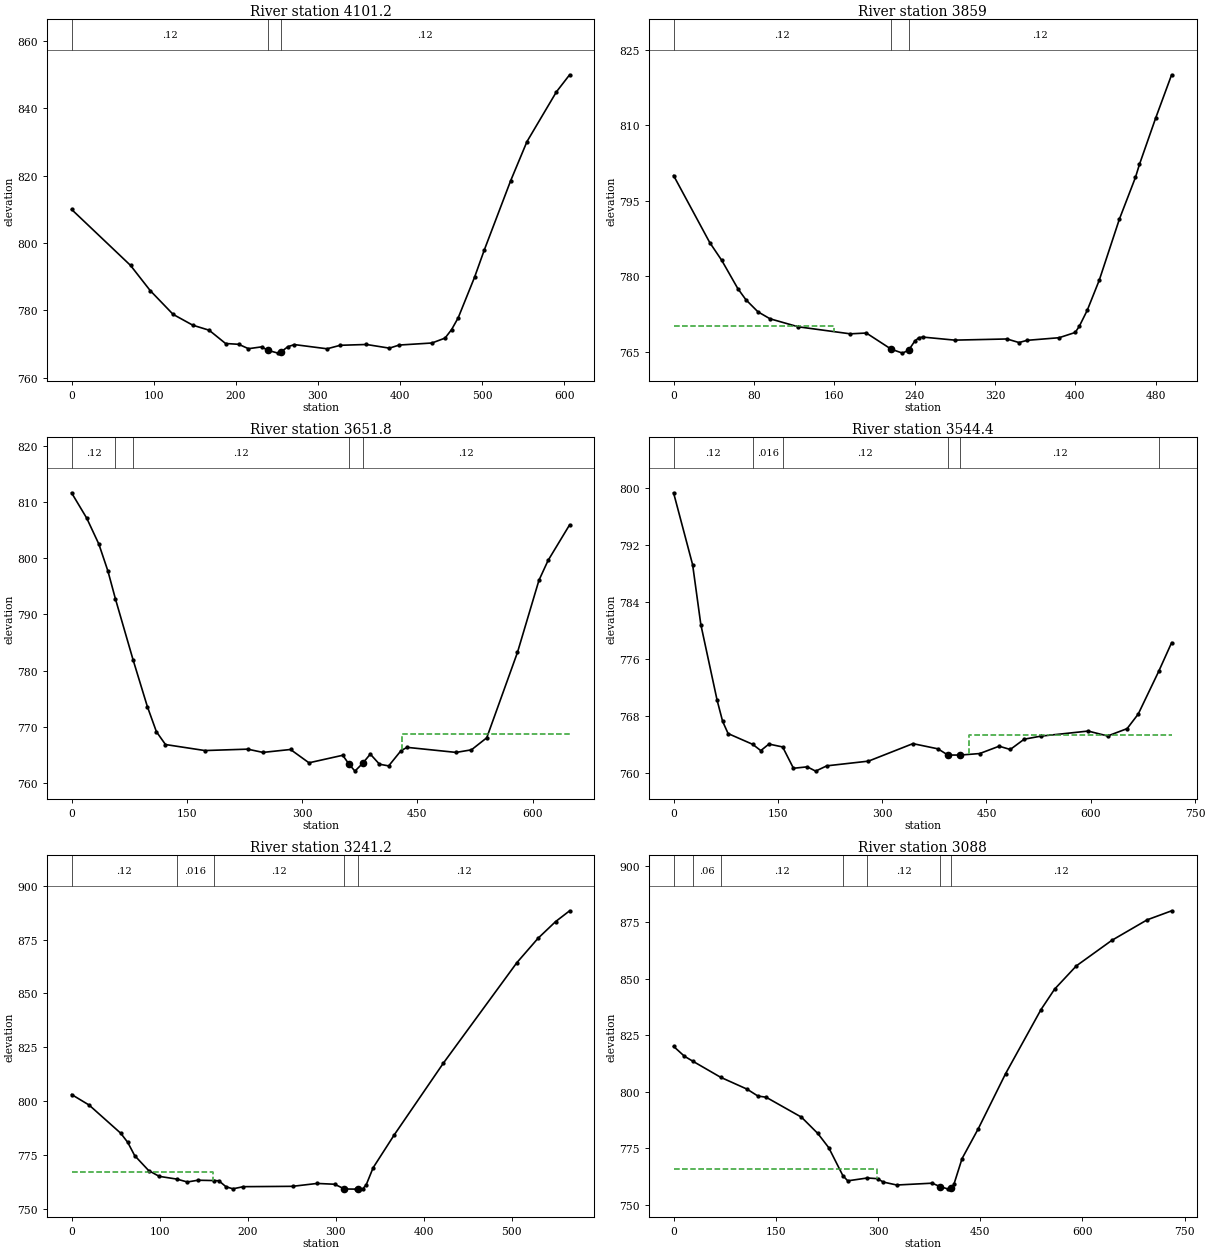
Type RM Length L Ch R = 1 ,4101.2  ,247.7,242.1,236.5
XS GIS Cut Line= 2
     2310880.114       362626.43     2310277.966      362700.537
#Sta/Elev= 30
       0     810    71.8  793.36    95.8  785.87   123.7   778.8   147.7  775.58
   167.6  774.09   187.6  770.14   203.6   769.9   215.5   768.6   231.5  769.14
   239.2  768.11   251.5  767.28   255.4  767.67   263.4  769.18   271.4  769.82
   311.3  768.57   327.3  769.61   359.2  769.85   387.2  768.76   399.1  769.68
     439  770.29     455  771.75     463   774.3     471  777.78   490.9  789.82
   502.9  798.01   534.8  818.46   554.8  830.16   590.7  844.96   606.7     850
#Mann= 3 ,-1 , 0
       0     .12       0   239.2    .045       0   255.4     .12       0
Bank Sta=239.2,255.4
XS Rating Curve= 0 ,0
Exp/Cntr=0.3,0.1

Type RM Length L Ch R = 1 ,3859    ,215.7,207.3,200.1
XS GIS Cut Line= 2
     2310780.114      362343.222     2310317.723      362522.145
#Sta/Elev= 30
       0     800      36  786.69      48  783.14      64  777.54      72  775.34
      84  772.94      96  771.56     124  769.97   175.9  768.57   191.9  768.73
   216.6  765.53   227.9  764.74  234.07765.3369   239.9  767.06   243.9  767.78
   247.9  767.93   279.9  767.32   331.9  767.55   343.9  766.84   351.9  767.28
   383.8   767.8   399.8  768.84   403.8  770.03   411.8  773.23   423.8  779.23
   443.8  791.33   459.8  799.62   463.8  802.21   479.8  811.33   495.8  819.99
#Mann= 3 ,-1 , 0
       0     .12       0   216.6    .045       0  234.07     .12       0
#XS Ineff= 2 , 0
          159.96  770.14
Permanent Ineff=
       F       F
Bank Sta=216.6,234.07
XS Rating Curve= 0 ,0
Exp/Cntr=0.3,0.1

Type RM Length L Ch R = 1 ,3651.8  ,108.1,107.4,105.4
XS GIS Cut Line= 3
     2310809.554      362222.063     2310644.053      362114.874
     2310297.036      362402.597
#Sta/Elev= 30
       0  811.64    19.7  807.14    35.5  802.52    47.3  797.72   57.06792.7737
   80.03781.9327    98.6  773.62   110.4  769.14   122.2  766.86   173.5  765.79
   229.1  766.04     249  765.46   284.9  765.98   308.9  763.61   352.8  764.95
   360.7  763.43   368.7  762.13   378.9  763.54   388.7  765.16   400.6  763.36
   412.6  763.06   428.6  765.76   436.5  766.36   500.4  765.46   520.3  765.92
   540.2  768.06   580.2  783.26   608.1  796.07     620  799.61     648  805.94
#Mann= 5 ,-1 , 0
       0     .12       0   57.06     .06       0   80.03     .12       0
   360.7    .045       0   378.9     .12       0
#XS Ineff= 2 , 0
                          430.55          768.72
Permanent Ineff=
       F       F
Bank Sta=360.7,378.9
XS Rating Curve= 0 ,0
Exp/Cntr=0.3,0.1

Type RM Length L Ch R = 1 ,3544.4  ,269.2,303.1,336.9
XS GIS Cut Line= 3
     2310804.813      362074.827     2310659.795      361974.606
      2310246.18      362321.642
#Sta/Elev= 30
       0   799.3    27.4  789.23    39.2  780.85    62.7  770.22    70.5  767.31
    78.4  765.59  113.89764.0767   125.4   763.2   137.1  764.12  156.86763.7145
   172.4  760.73   192.3  760.93   204.3  760.33   220.3  761.07   280.3  761.73
   344.2  764.18   380.2  763.45  394.48762.5836   412.2  762.58   440.2  762.79
   468.2  763.82   484.2  763.36   504.2   764.8   528.2  765.23   596.2  765.94
   624.2  765.25   652.2  766.28   668.2  768.32  697.61774.2908   716.2  778.31
#Mann= 6 ,-1 , 0
       0     .12       0  113.89    .016       0  156.86     .12       0
  394.48    .045       0   412.2     .12       0  697.61    .016       0
#XS Ineff= 2 , 0
                          424.36          765.34
Permanent Ineff=
       F       F
Bank Sta=394.48,412.2
XS Rating Curve= 0 ,0
Exp/Cntr=0.3,0.1

Type RM Length L Ch R = 1 ,3241.2  ,148.4,153.2,158.3
XS GIS Cut Line= 2
     2310833.368      362061.365      2310408.02      361688.101
#Sta/Elev= 30
       0  803.07    19.9  798.18    55.8  785.11    63.8  780.86    71.7   774.7
    87.7  767.71    99.6  765.06  119.75  763.78   131.5  762.44   143.5  763.26
  161.73763.1082   167.4  763.01   175.4  760.25   183.3  759.28   195.3  760.27
   251.1  760.43     279  761.77   298.9   761.4   310.1   759.2   322.8  759.13
   325.1  759.15   330.8  759.25   334.8  761.14   342.7  769.09   366.6  784.29
   422.4  817.59   506.1  864.35     530  875.59     550  883.36   565.9  888.36
#Mann= 5 ,-1 , 0
       0     .12       0  119.75    .016       0  161.73     .12       0
   310.1    .045       0   325.1     .12       0
#XS Ineff= 2 , 0
          160.99  767.03
Permanent Ineff=
       F       F
Bank Sta=310.1,325.1
XS Rating Curve= 0 ,0
Exp/Cntr=0.3,0.1

Type RM Length L Ch R = 1 ,3088    ,132.1,147.7,163
XS GIS Cut Line= 2
     2310966.843      362131.266     2310549.276      361531.375
#Sta/Elev= 30
       0  820.01      16  815.63   28.84813.3468   69.14 806.323   107.8  801.09
   123.8  798.03   135.8  797.51   187.7  788.68   211.7  781.47   227.7  775.19
  248.44762.8205   255.6  760.51  284.53761.7767   299.6  761.45   307.5  759.99
   327.5  758.66   379.4  759.47   390.9  757.99   403.4  756.84   407.4  757.16
   411.4  758.95   423.4  770.38   447.3  783.64   487.3  807.96   539.2  836.29
   559.2  845.34   591.1  855.64     643   866.9     695  876.01   730.9     880
#Mann= 7 ,-1 , 0
       0     .12       0   28.84     .06       0   69.14     .12       0
  248.44    .016       0  284.53     .12       0   390.9    .045       0
   407.4     .12       0
#XS Ineff= 2 , 0
          298.47  765.72
Permanent Ineff=
       F       F
Bank Sta=390.9,407.4
XS Rating Curve= 0 ,0
Exp/Cntr=0.3,0.1

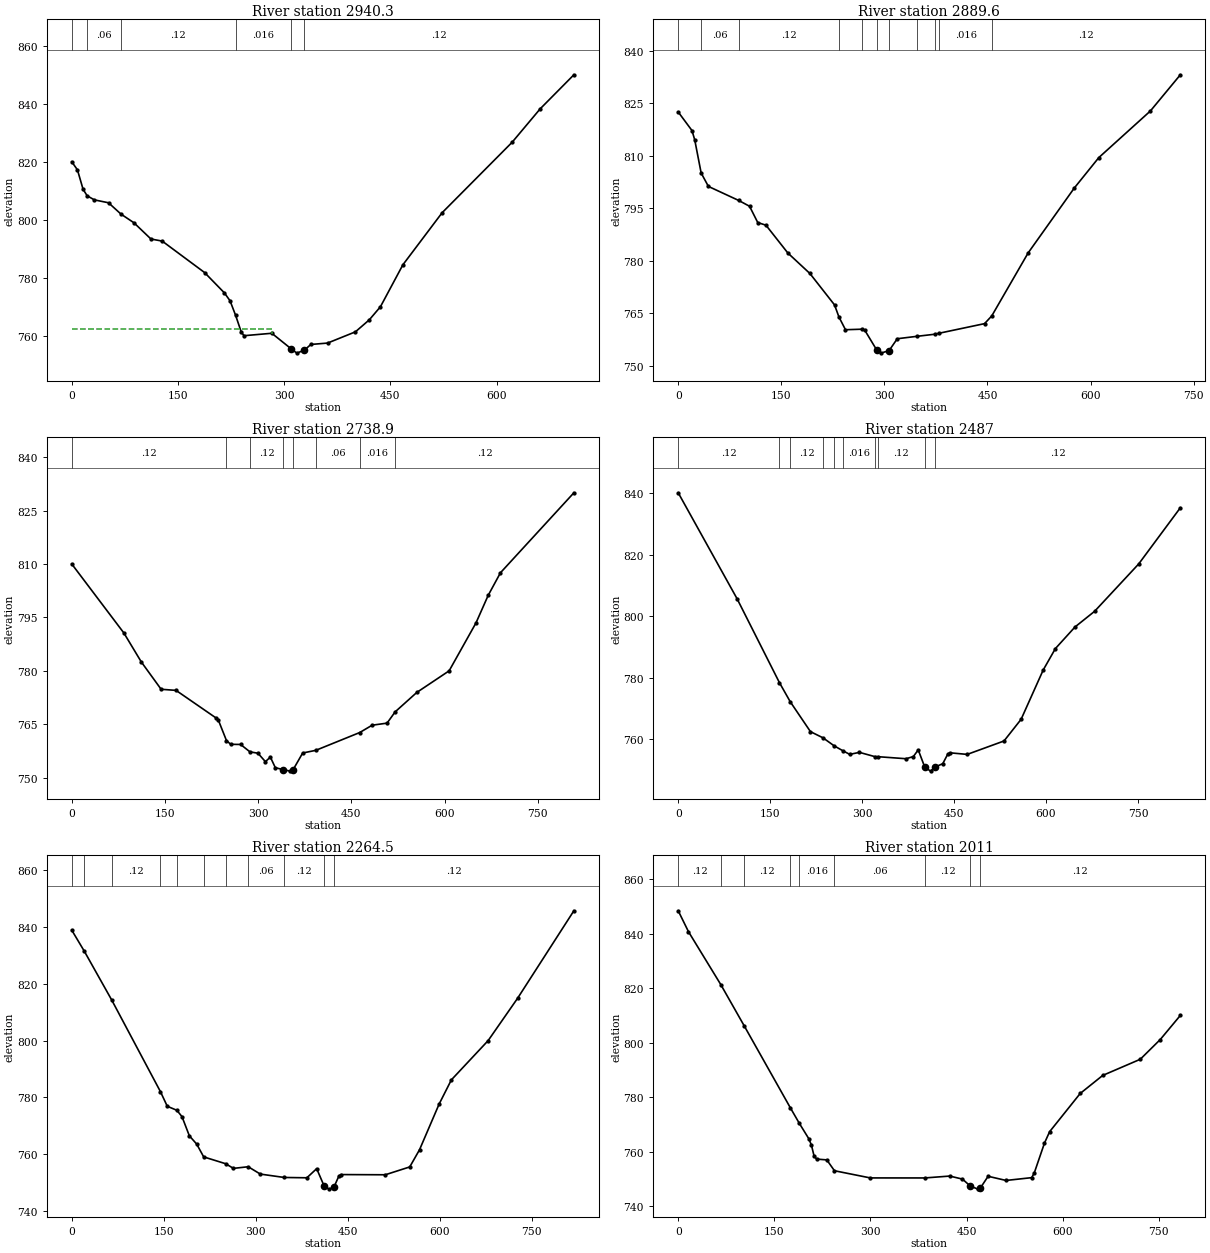
Type RM Length L Ch R = 1 ,2940.3  ,50.6,50.7,50.8
XS GIS Cut Line= 4
     2311010.277      362104.537     2310880.963      361917.386
     2310888.695      361709.119       2310658.2      361562.623
#Sta/Elev= 30
       0     820       8  817.22      16  810.49   21.77808.2607    31.9  806.86
    51.9  805.86   69.51801.9481    87.8  798.96   111.8  793.36   127.7  792.64
   187.6  781.78   215.5  774.78   223.5  772.05  231.26 767.098   239.3   761.3
   243.2     760   282.5  760.84   310.1  755.42   317.9  753.99   328.6  755.04
   337.6  756.98   361.2  757.46   400.5  761.33   420.2  765.49   435.9     770
   467.6  784.47     523  802.43   621.9  826.75   661.5  838.28     709     850
#Mann= 6 ,-1 , 0
       0     .12       0   21.77     .06       0   69.51     .12       0
  231.26    .016       0   310.1    .045       0   328.6     .12       0
#XS Ineff= 2 , 0
           283.2  762.22
Permanent Ineff=
       F       F
Bank Sta=310.1,328.6
XS Rating Curve= 0 ,0
Exp/Cntr=0.3,0.1

Type RM Length L Ch R = 1 ,2889.6  ,166.4,150.7,135.1
XS GIS Cut Line= 4
     2311060.473      362094.829     2310931.159      361907.678
     2310941.345      361661.768     2310708.396      361552.915
#Sta/Elev= 30
       0  822.47      20  817.18      24  814.53   33.35805.0583    43.9  801.23
   87.92797.2292   103.8  795.56   115.7  790.92   127.7  790.15   159.6   782.2
   191.6  776.37   227.5  767.39  233.87763.9509   243.4  760.31  267.14760.4615
   271.2  760.26  289.17754.4246     295  753.63   306.9  754.36   318.8  757.74
  346.99 758.418  373.28759.0224  380.19759.3303   445.8  762.05  456.32764.2629
   509.2  782.23   576.4  800.77   612.1  809.46   687.2  822.78   730.7  833.09
#Mann= 11 ,-1 , 0
       0     .12       0   33.35     .06       0   87.92     .12       0
  233.87    .016       0  267.14     .12       0  289.17    .045       0
   306.9     .12       0  346.99    .016       0  373.28     .06       0
  380.19    .016       0  456.32     .12       0
Bank Sta=289.17,306.9
XS Rating Curve= 0 ,0
Exp/Cntr=0.3,0.1

Type RM Length L Ch R = 1 ,2738.9  ,251.6,251.9,252.2
XS GIS Cut Line= 3
     2311268.565      362048.086     2310909.739      361558.162
     2310716.301      361504.537
#Sta/Elev= 30
       0  810.01    83.9  790.62   111.9   782.5   143.8  774.82   167.8  774.51
   231.7  766.82   235.7  766.25  248.92 760.431   255.7  759.36   271.7  759.32
  286.78757.2437   299.6  756.86   311.6  754.49   319.6  755.77   327.6  752.79
   340.1  752.26   351.6  751.83   355.6  752.04   371.6  756.92  392.69757.6687
  463.36762.6662   483.4  764.73   507.4  765.31  520.44 768.482   555.3  773.94
   607.3     780   650.6  793.49   670.2  801.22   689.9  807.55     808     830
#Mann= 8 ,-1 , 0
       0     .12       0  248.92    .016       0  286.78     .12       0
   340.1    .045       0   355.6     .12       0  392.69     .06       0
  463.36    .016       0  520.44     .12       0
Bank Sta=340.1,355.6
XS Rating Curve= 0 ,0
Exp/Cntr=0.3,0.1

Type RM Length L Ch R = 1 ,2487    ,222.5,222.5,222.5
XS GIS Cut Line= 2
     2311506.415      361955.237      2311030.75      361288.526
#Sta/Elev= 30
       0  840.17    95.9   805.7  165.11778.3281  182.77772.1016   215.7  762.38
  236.18760.3632  254.45757.7438   269.2 756.085   279.7  754.98   295.6  755.63
  321.24754.2154  326.13 754.218   371.6  753.56   383.5  754.26   391.5  756.44
     402  750.89   411.5  749.52   419.5  750.91   431.5  751.94   439.5     755
   443.5  755.48   471.4  754.97   531.4  759.34   559.3   766.4   595.3  782.44
   615.2  789.43   647.2  796.47   679.2  801.58   751.1     817     819  835.29
#Mann= 10 ,-1 , 0
       0     .12       0  165.11     .06       0  182.77     .12       0
  236.18     .06       0  254.45     .12       0   269.2    .016       0
  321.24     .06       0  326.13     .12       0     402    .045       0
   419.5     .12       0
Bank Sta=402,419.5
XS Rating Curve= 0 ,0
Exp/Cntr=0.3,0.1

Type RM Length L Ch R = 1 ,2264.5  ,253.5,253.5,253.5
XS GIS Cut Line= 2
     2311691.306      361831.252     2311215.641      361164.541
#Sta/Elev= 30
       0  838.87   20.47831.4656   65.15814.3038  144.56782.0896   155.8  776.91
  171.41 775.501   179.8  773.26   191.8  766.52   203.8   763.6  215.19759.0979
  251.03756.6985   263.7  755.06  287.81755.6348   307.6  753.05  346.69751.8605
   383.5  751.75   399.5  754.96   411.5  748.94   419.5  747.76   427.5   748.4
   435.5  752.25   439.5  752.88   511.4  752.81   551.3  755.57   567.3  761.63
   599.3  777.72   619.2   786.2   679.2  800.02   727.1  814.87     819  845.68
#Mann= 11 ,-1 , 0
       0     .12       0   20.47    .016       0   65.15     .12       0
  144.56     .06       0  171.41     .12       0  215.19     .06       0
  251.03    .016       0  287.81     .06       0  346.69     .12       0
   411.5    .045       0   427.5     .12       0
Bank Sta=411.5,427.5
XS Rating Curve= 0 ,0
Exp/Cntr=0.3,0.1

Type RM Length L Ch R = 1 ,2011    ,250.7,250.8,250.7
XS GIS Cut Line= 3
     2311921.345       361717.39     2311561.465      361212.967
     2311552.762      361049.185
#Sta/Elev= 30
       0  848.37      16  840.71   66.37821.3416  103.42806.0044  174.94776.1616
  189.12770.3893   203.9  764.76   207.9  762.44   211.9  758.59   215.9  757.33
   231.9  757.03  243.86753.0524   299.8  750.42  384.79750.4099   423.8   751.1
   443.7  749.98   455.7  747.47   467.7  746.31   471.7  746.76   483.7  751.02
   511.7  749.49   551.7  750.52   555.7  752.22   571.7  763.21   579.7  767.37
   627.4  781.38   662.6  788.01   721.2  793.93   752.4  801.17   783.7     810
#Mann= 9 ,-1 , 0
       0     .12       0   66.37    .016       0  103.42     .12       0
  174.94     .06       0  189.12    .016       0  243.86     .06       0
  384.79     .12       0   455.7    .045       0   471.7     .12       0
Bank Sta=455.7,471.7
XS Rating Curve= 0 ,0
Exp/Cntr=0.3,0.1

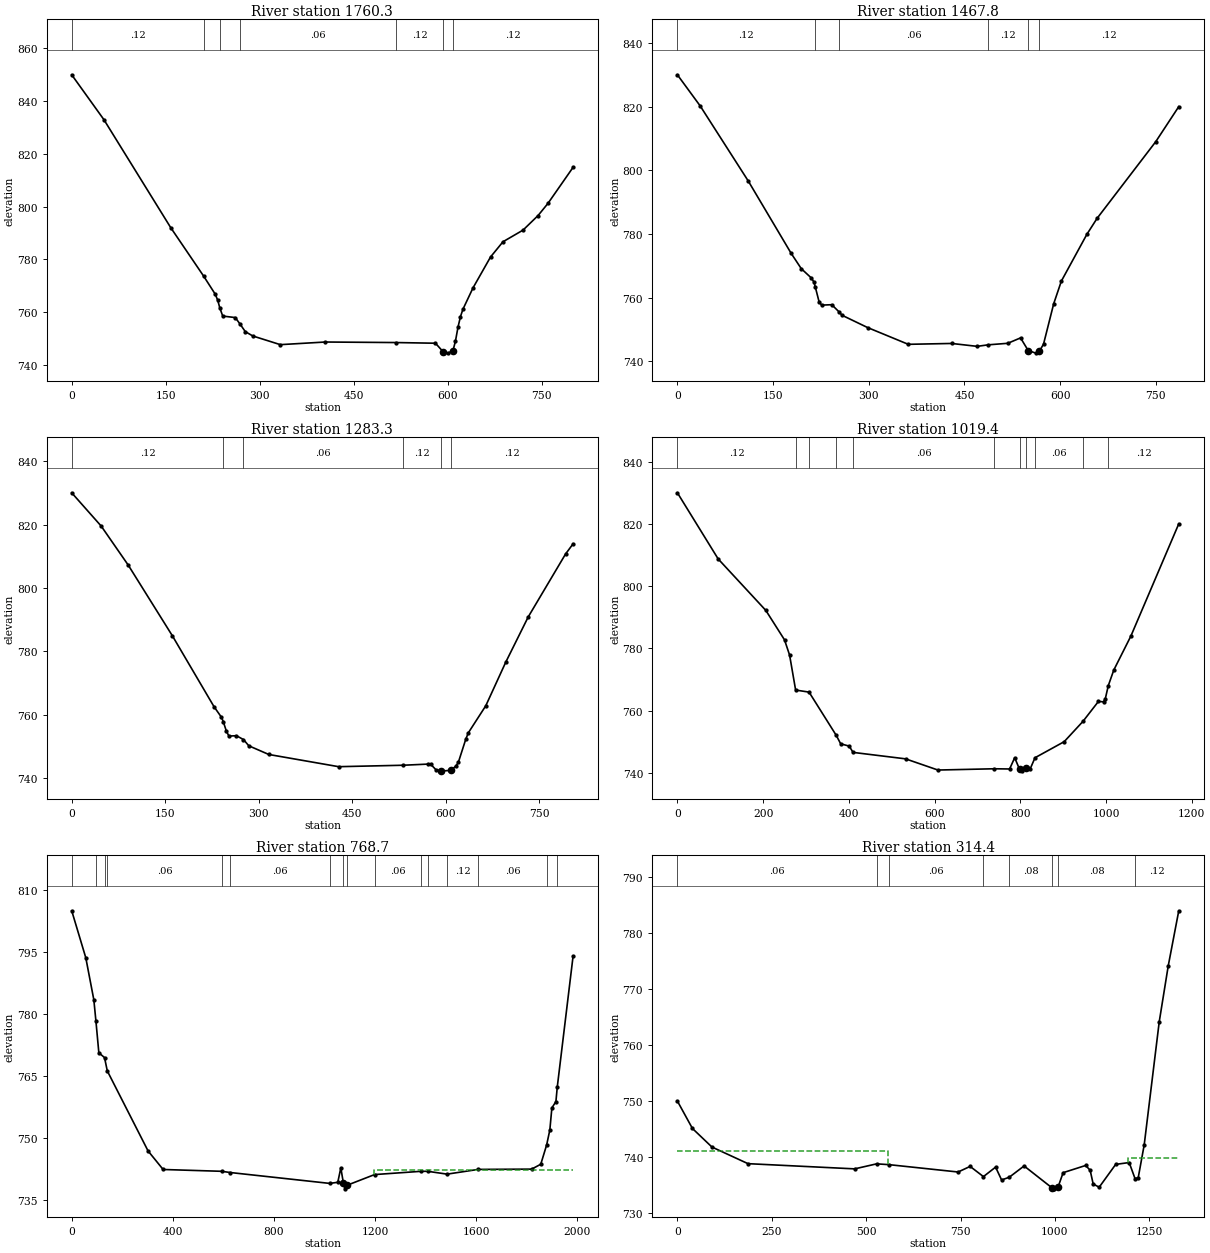
Type RM Length L Ch R = 1 ,1760.3  ,290.6,292.5,294.5
XS GIS Cut Line= 3
     2312100.206      361660.445     2312022.254      361457.743
     2311683.527       360982.97
#Sta/Elev= 30
       0     850    51.3     833     158  791.99  210.79773.5001   229.2  766.67
   233.2  764.33  236.47 761.436   241.1   758.4   261.1  757.83  268.69755.3712
   277.1  752.49   289.1  750.84     333  747.55   404.9  748.55  517.87748.3453
   580.7  748.09   592.7  744.91   600.7  744.33   608.6  745.24   612.6  748.88
   616.6  754.12   620.6   758.2   624.6  761.02   640.6  769.09   668.6  780.83
   688.5  786.62   720.5  791.04   744.5  796.57   760.4  801.22   800.4  814.88
#Mann= 7 ,-1 , 0
       0     .12       0  210.79     .06       0  236.47    .016       0
  268.69     .06       0  517.87     .12       0   592.7    .045       0
   608.6     .12       0
Bank Sta=592.7,608.6
XS Rating Curve= 0 ,0
Exp/Cntr=0.3,0.1

Type RM Length L Ch R = 1 ,1467.8  ,184.1,184.5,184.8
XS GIS Cut Line= 3
     2312266.195      361570.619     2312246.212      361353.576
     2311964.364      360860.537
#Sta/Elev= 30
       0     830    35.7  820.23     111  796.65   178.3   773.9   194.2  769.07
     210  766.14     214  764.88  216.34763.1835     222  758.73     226  757.62
     242  757.75  253.03755.5686     258  754.44     298  750.58   361.9   745.3
   429.9  745.57   469.9  744.66   487.2 745.139   517.9  745.62   537.9  747.32
   549.9  743.34   561.9  742.53   567.2  743.06   573.9  745.34   589.9  758.08
   601.9  765.18   641.9  779.88   657.9   784.9   749.9  809.01   785.9     820
#Mann= 6 ,-1 , 0
       0     .12       0  216.34    .016       0  253.03     .06       0
   487.2     .12       0   549.9    .045       0   567.2     .12       0
Bank Sta=549.9,567.2
XS Rating Curve= 0 ,0
Exp/Cntr=0.3,0.1

Type RM Length L Ch R = 1 ,1283.3  ,261.7,263.8,265.7
XS GIS Cut Line= 3
     2312402.362      361554.785     2312431.976       361320.59
     2312150.128      360827.551
#Sta/Elev= 30
       0     830    47.2  819.53    90.5  807.25   161.3  784.97   228.2  762.59
   240.1  759.27  242.95757.9234   248.1  754.83   252.1  753.34   264.1  753.45
  275.37752.2481     284  750.27     316  747.54     428  743.69  531.32744.1432
     572  744.51     576  744.38     584  742.74     592  742.29   592.7   742.3
   607.7  742.54     616  743.86     620  745.06     632   752.4     636  754.36
     664  762.89     696  776.62     732  790.87     792  810.74     804  813.92
#Mann= 6 ,-1 , 0
       0     .12       0  242.95    .016       0  275.37     .06       0
  531.32     .12       0   592.7    .045       0   607.7     .12       0
Bank Sta=592.7,607.7
XS Rating Curve= 0 ,0
Exp/Cntr=0.3,0.1

Type RM Length L Ch R = 1 ,1019.4  ,249.1,250.8,252.4
XS GIS Cut Line= 4
     2312489.895      361592.537     2312688.608      361325.032
     2312451.212      360807.635     2312191.206      360745.445
#Sta/Elev= 30
       0     830    95.2  808.73   206.3   792.2   249.9  782.74   261.8  777.82
  275.85766.5948  307.17 765.933  370.53752.0494     381  749.31   400.9  748.57
  409.83746.5536   532.3  744.48   607.9  740.88  739.07741.2871   775.1  741.22
     787  744.84   798.5  741.07     803  740.53   813.5  741.44   822.9  741.17
  834.35744.8312   902.5     750  946.32756.5268   982.3  762.92   994.3  762.82
   998.3  763.73 1005.44 768.026  1018.2  773.02  1058.1  783.95  1169.8  820.02
#Mann= 11 ,-1 , 0
       0     .12       0  275.85    .016       0  307.17     .06       0
  370.53    .016       0  409.83     .06       0  739.07     .12       0
   798.5    .045       0   813.5     .12       0  834.35     .06       0
  946.32    .016       0 1005.44     .12       0
Bank Sta=798.5,813.5
XS Rating Curve= 0 ,0
Exp/Cntr=0.3,0.1

Type RM Length L Ch R = 1 ,768.7   ,419.7,454.3,489
XS GIS Cut Line= 4
     2312650.283      361647.095     2312975.861       361472.79
     2312576.114        360407.3     2312113.296      360515.356
#Sta/Elev= 30
       0  804.95    55.6   793.6    87.4  783.43   95.61778.3182   107.2  770.62
  129.69769.4518  140.59766.2356   301.8  746.88   361.4  742.39  593.61  741.95
  626.01741.6609 1019.97739.0257  1052.1  739.29  1064.1  742.78  1074.1  739.18
  1080.1  737.64  1089.1  738.58 1197.54 741.159 1380.38741.9444 1407.87741.9474
 1484.38741.2647 1607.29742.4086  1818.8  742.48  1854.8  743.66 1878.09748.3395
  1890.7  751.97  1898.7  757.28  1914.7  758.82 1920.08762.3489  1982.6  793.99
#Mann= 16 ,-1 , 0
       0     .12       0   95.61    .016       0  129.69     .12       0
  140.59     .06       0  593.61    .016       0  626.01     .06       0
 1019.97     .12       0  1074.1    .045       0  1089.1     .12       0
 1197.54     .06       0 1380.38    .016       0 1407.87     .06       0
 1484.38     .12       0 1607.29     .06       0 1878.09    .016       0
 1920.08     .12       0
#XS Ineff= 2 , 0
                         1193.34          742.25
Permanent Ineff=
       F       F
Bank Sta=1074.1,1089.1
XS Rating Curve= 0 ,0
Exp/Cntr=0.3,0.1

Type RM Length L Ch R = 1 ,314.4   ,337,314.4,291.6
XS GIS Cut Line= 4
     2312930.182      361688.537     2313156.114      361380.447
     2312989.771       360878.88     2313366.302       360698.35
#Sta/Elev= 30
       0     750    39.8  745.11    91.5  741.79     187  738.82   469.5  737.89
  527.77 738.787  560.64738.6421   743.6  737.33   775.4  738.33  810.67736.5071
   842.9   738.2   858.8  735.91  878.99 736.389   918.4  738.41   993.2  734.45
     998  734.27  1008.2  734.61  1021.8  737.21  1081.5   738.5  1093.4  737.64
  1101.4  735.19  1117.3  734.61    1161  738.69  1196.8  739.02 1212.29736.1473
  1220.7   736.3  1236.6  742.19  1276.4  764.18  1300.2  774.15  1328.1     784
#Mann= 8 ,-1 , 0
       0     .06       0  527.77    .016       0  560.64     .06       0
  810.67     .12       0  878.99     .08       0   993.2    .045       0
  1008.2     .08       0 1212.29     .12       0
#XS Ineff= 2 , 0
          557.94  741.03 1192.65           739.9
Permanent Ineff=
       F       F
Bank Sta=993.2,1008.2
XS Rating Curve= 0 ,0
Exp/Cntr=0.3,0.1
LCMann Table=0

Chan Stop Cuts=-1
Use User Specified Reach Order=0
Composite Channel Slope=5